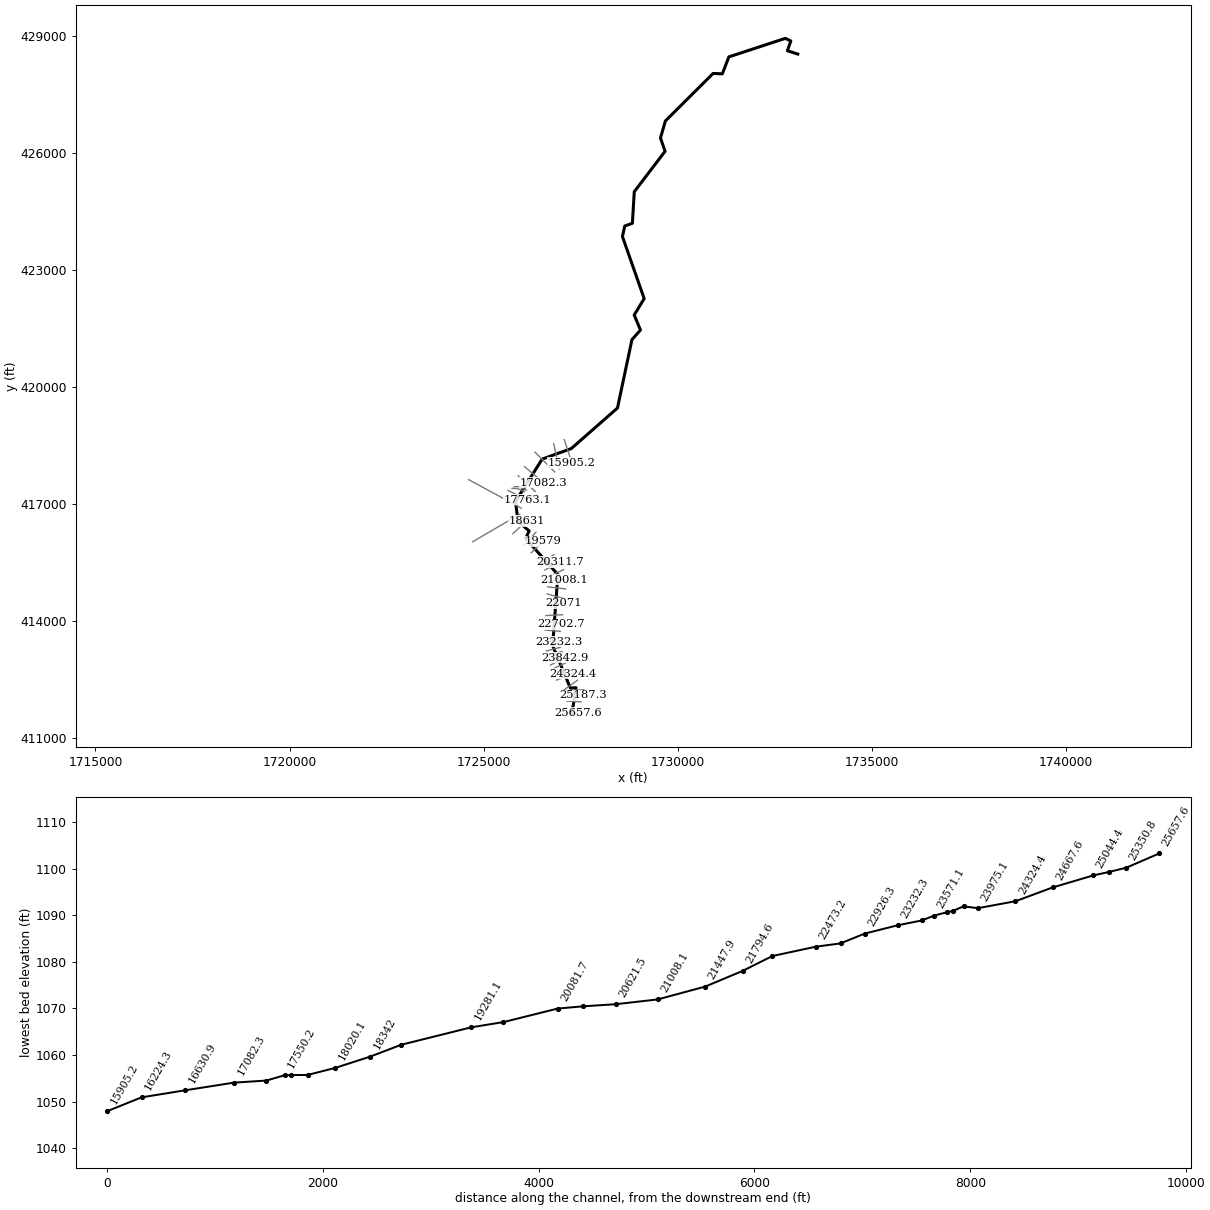
--- SouthFork.prj (project) ---

Proj Title=SouthFork
Current Plan=p01
Default Exp/Contr=0,0
English Units
Geom File=g01
Flow File=f01
Plan File=p01
BEGIN DESCRIPTION:
END DESCRIPTION:
DSS Export Rating Curves= 0
DSS Export Rating Curve Sorted= 0
DSS Export Volume Flow Curves= 0
DXF OffsetX= 0
DXF OffsetY= 0
DXF ScaleX= 0
DXF ScaleY= 0

--- SouthFork.p01 (plan) ---

Plan Title=Floodplain
Program Version=4.00
Geom File=g01
Flow File=f01
K Sum by GR=0
Std Step Tol=0.01
Critical Tol=0.01
Num of Std Step Trials=20
Max Error Tol=0.3
Flow Tol Ratio=0.001
Split Flow NTrial=30
Split Flow Tol=0.02
Split Flow Ratio=0.02
Log Output Level=0
Friction Slope Method=1
Unsteady Friction Slope Method=2
Unsteady Bridges Friction Slope Method=1
Global Log Level=0
CheckData=False
Run HTab=0
Run UNet=0
Run PostProcess=0
UNET Theta=0
UNET Theta Warmup=0
UNET ZTol=0
UNET ZSATol=0
UNET MxIter=0
UNET MaxInSteps=0
UNET DtIC=0
UNET DtMin=0
UNET MaxCRTS=0
UNET WFStab=0
UNET SFStab=0
UNET WFX=0
UNET SFX=0
UNET DSS MLevel=0
UNET DZMax Abort=0
UNET Convert EG Bridges=0
UNET Use Existing IB Tables=0
UNET Froude Limit=0
UNET Froude Power=0
Write IC File=0
Echo Input=False
Echo Output=False
Write Detailed=0

--- SouthFork.f01 (steady flow) ---

Flow Title=NFF Regression Equation
Program Version=4.00
Number of Profiles=1
Profile Names=P100yr
River Rch & RM=SouthFork,Main      ,25657.6
     825
River Rch & RM=SouthFork,Main      ,17611.2
    1282
River Rch & RM=SouthFork,Main      ,15905.2
    1341
River Rch & RM=SouthFork,Main      ,14284.9
    1395
River Rch & RM=SouthFork,Main      ,11694.7
    1515
River Rch & RM=SouthFork,Main      ,5543.5
    1618
River Rch & RM=SouthFork,Main      ,3901.3
    1872
River Rch & RM=SouthFork,Main      ,3530.8
    1878
River Rch & RM=SouthFork,Main      ,1064.2
    3469
Boundary for River Rch & Prof#=SouthFork,Main      ,1
Up Type=0
Dn Type=3
Dn Slope=0.005912

--- SouthFork.g01 (geometry) ---

Geom Title=USGS 10m DEM
Program Version=4.10

River Reach=SouthFork       ,Main
Reach XY= 30
     1727279.986      411637.671     1727381.966       412295.92
     1727239.385      412284.534     1726780.949      413375.275
     1726917.496      415196.078     1726086.221      416121.968
     1726175.621      416317.606     1725888.728      416560.183
     1725824.605      417073.286     1726512.089      418160.388
     1727262.089      418429.485     1728452.518      419469.706
     1728825.093      421222.608     1729045.075      421471.152
     1728883.329      421855.152     1729140.561      422276.273
     1728580.522      423867.959     1728640.561      424138.353
     1728836.742      424208.999     1728885.353      425018.027
     1729679.023      426054.753       1729560.7      426396.499
     1729687.436      426832.263     1730917.041      428051.328
     1731156.187      428042.333     1731322.853      428476.361
      1732779.45      428952.055     1732920.075       428882.61
     1732831.534      428634.346     1733098.581       428548.07

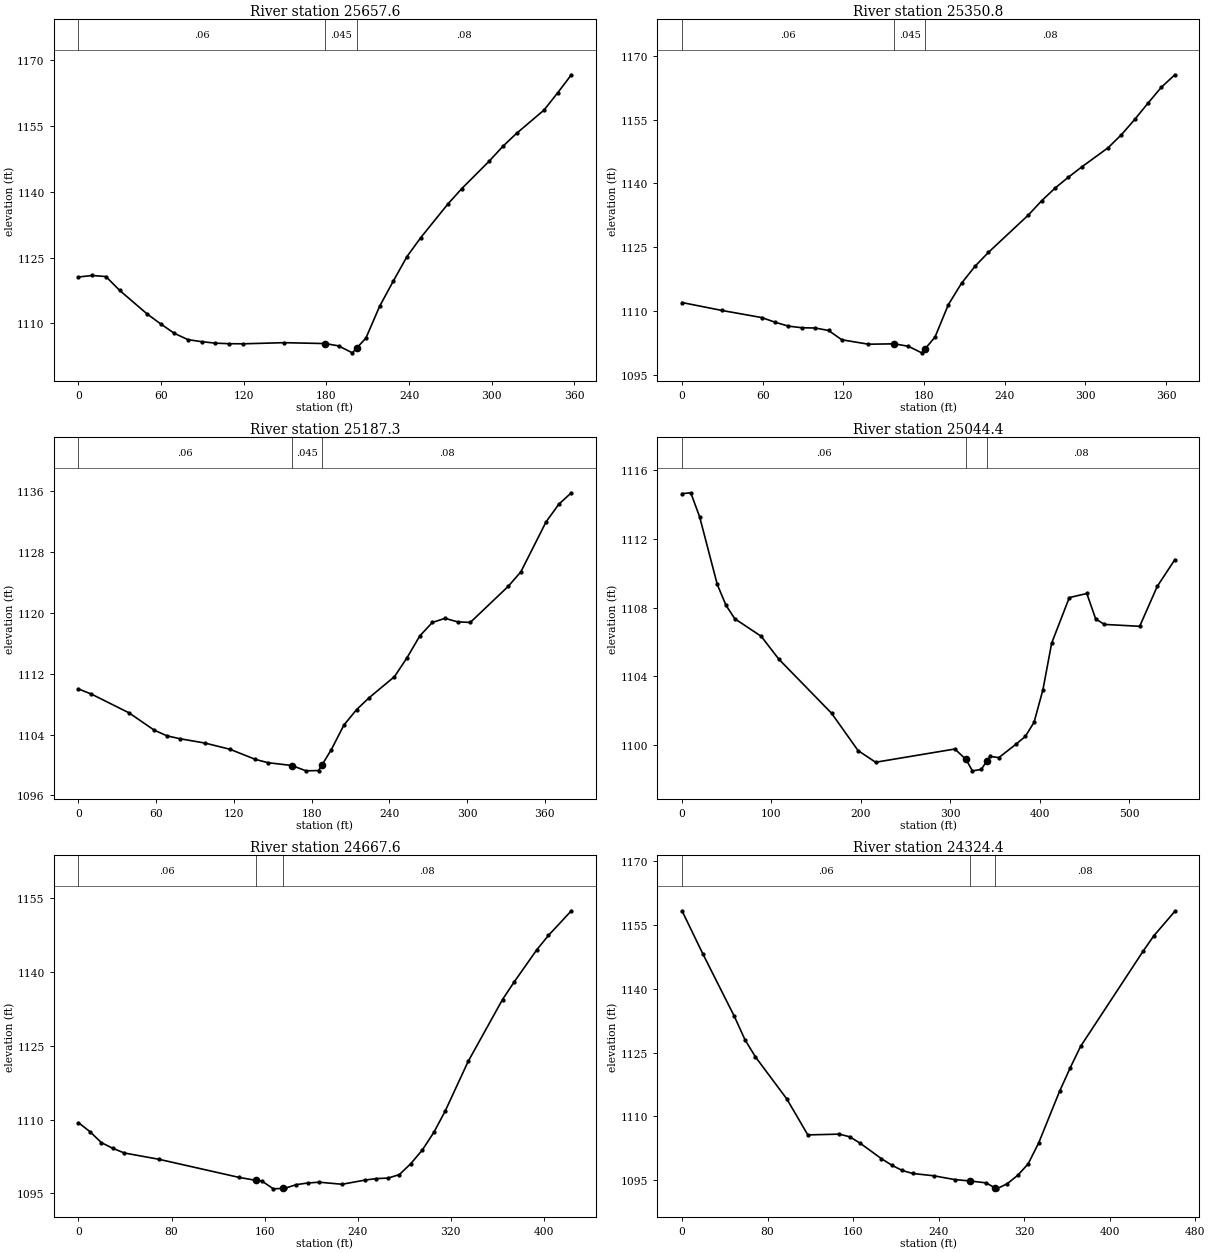
Type RM Length L Ch R = 1 ,25657.6 ,308.9,306.8,304.2
XS GIS Cut Line= 2
     1727087.967       411637.39     1727445.581      411647.916
#Sta/Elev= 30
       0 1120.56     9.9  1120.9    19.9 1120.66    29.8 1117.52    49.7 1112.15
    59.6 1109.86    69.6 1107.69    79.5 1106.25    89.4 1105.79    99.4 1105.45
   109.3 1105.33   119.3  1105.3   149.1 1105.56   179.1 1105.36   188.8 1104.83
   198.8 1103.24   202.1 1104.37   208.7 1106.63   218.6 1113.86   228.6 1119.66
   238.5 1125.23   248.4 1129.52   268.3 1137.27   278.3 1140.76   298.1 1146.99
   308.1 1150.39     318 1153.35   337.9 1158.65   347.8 1162.58   357.8 1166.73
#Mann= 3 , 0 , 0
       0     .06       0   179.1    .045       0   202.1     .08       0
Bank Sta=179.1,202.1
XS Rating Curve= 0 ,0
Exp/Cntr=0.3,0.1

Type RM Length L Ch R = 1 ,25350.8 ,160.3,163.5,165.3
XS GIS Cut Line= 2
     1727148.206      411950.755      1727514.31      411932.651
#Sta/Elev= 30
       0    1112    29.7 1110.14    59.4 1108.46    69.4 1107.35    79.2 1106.45
    89.2 1106.07    99.1 1106.01     109 1105.43   118.9 1103.24   138.7  1102.2
     158 1102.29   168.4 1101.71   178.3 1100.17     181 1101.18   188.2 1103.88
   198.1 1111.49     208 1116.57     218 1120.54   227.9 1123.79   257.6 1132.57
   267.5 1135.93   277.4 1138.89   287.3 1141.45   297.2 1143.86     317 1148.42
   326.9 1151.49   336.8 1155.08   346.7 1158.93   356.6 1162.65   366.6 1165.57
#Mann= 3 , 0 , 0
       0     .06       0     158    .045       0     181     .08       0
Bank Sta=158,181
XS Rating Curve= 0 ,0
Exp/Cntr=0.3,0.1

Type RM Length L Ch R = 1 ,25187.3 ,145.3,142.9,144.3
XS GIS Cut Line= 2
     1727175.901      412094.824     1727556.161      412106.035
#Sta/Elev= 30
       0    1110     9.8 1109.34      39 1106.86    58.5 1104.58    68.3 1103.84
      78 1103.47    97.6 1102.89     117 1102.07   136.6 1100.74   146.3 1100.31
   164.7 1099.94   175.6 1099.24   185.3 1099.28   187.7 1099.95   195.1 1102.01
   204.8 1105.24   214.6 1107.28   224.4 1108.86   243.9 1111.62   253.6 1114.11
   263.4 1116.96   273.1 1118.74   282.9 1119.28   292.6 1118.82   302.4 1118.74
   331.6 1123.47   341.4 1125.38   360.9 1131.96   370.7 1134.27   380.4 1135.78
#Mann= 3 , 0 , 0
       0     .06       0   164.7    .045       0   187.7     .08       0
Bank Sta=164.7,187.7
XS Rating Curve= 0 ,0
Exp/Cntr=0.3,0.1

Type RM Length L Ch R = 1 ,25044.4 ,354.3,376.8,241.8
XS GIS Cut Line= 2
     1727034.786      412208.221     1727584.417      412245.753
#Sta/Elev= 30
       0 1114.64     9.8 1114.69    19.7 1113.29    39.4 1109.36    49.2 1108.14
      59 1107.36    88.5 1106.34   108.2 1105.01   167.2 1101.86   196.8 1099.69
   216.4 1099.01     305 1099.78   317.5 1099.17   324.6 1098.51   334.5 1098.59
   340.5 1099.06   344.3 1099.35   354.2 1099.28   373.8 1100.08   383.7 1100.51
   393.5 1101.33   403.4 1103.22   413.2 1105.94   432.9 1108.59   452.5 1108.83
   462.4 1107.35   472.2 1107.03   511.6 1106.92   531.2 1109.24   550.9  1110.8
#Mann= 3 , 0 , 0
       0     .06       0   317.5    .045       0   340.5     .08       0
Bank Sta=317.5,340.5
XS Rating Curve= 0 ,0
Exp/Cntr=0.3,0.1

Type RM Length L Ch R = 1 ,24667.6 ,332.6,343.2,327.8
XS GIS Cut Line= 2
     1727077.701      412242.082     1727422.618      412488.451
#Sta/Elev= 30
       0 1109.38     9.9 1107.55    19.7 1105.33    29.6 1104.16    39.4 1103.22
      69 1101.95     138 1098.26   152.5 1097.66   157.7 1097.52   167.6 1095.93
   175.5 1096.02   177.4 1096.04   187.3 1096.78   197.2 1097.12     207 1097.28
   226.7 1096.86   246.4 1097.71   256.3 1098.02   266.2 1098.11     276 1098.83
   285.9 1101.07   295.7 1103.82   305.6  1107.4   315.4 1111.75   335.2 1121.87
   364.7 1134.43   374.6 1137.96   394.3 1144.59   404.2 1147.46   423.9 1152.48
#Mann= 3 , 0 , 0
       0     .06       0   152.5    .045       0   175.5     .08       0
Bank Sta=152.5,175.5
XS Rating Curve= 0 ,0
Exp/Cntr=0.3,0.1

Type RM Length L Ch R = 1 ,24324.4 ,324.5,349.3,362.6
XS GIS Cut Line= 2
     1726879.894      412491.703     1727310.178       412657.31
#Sta/Elev= 30
       0  1158.3    19.6 1148.13      49 1133.48    58.9 1128.01    68.7 1123.98
    98.1 1114.07   117.7 1105.65   147.1 1105.83     157  1105.2   166.8 1103.67
   186.4 1100.09   196.2 1098.54     206 1097.29   215.8 1096.59   235.4 1096.05
     255 1095.16   269.8 1094.82   284.5 1094.38   292.8 1093.19   294.3 1092.98
   304.1 1094.16   313.9 1096.13   323.7 1098.81   333.5 1103.69   353.2 1115.91
     363 1121.34   372.8 1126.43   431.6 1148.92   441.4 1152.44     461 1158.17
#Mann= 3 , 0 , 0
       0     .06       0   269.8    .045       0   292.8     .08       0
Bank Sta=269.8,292.8
XS Rating Curve= 0 ,0
Exp/Cntr=0.3,0.1

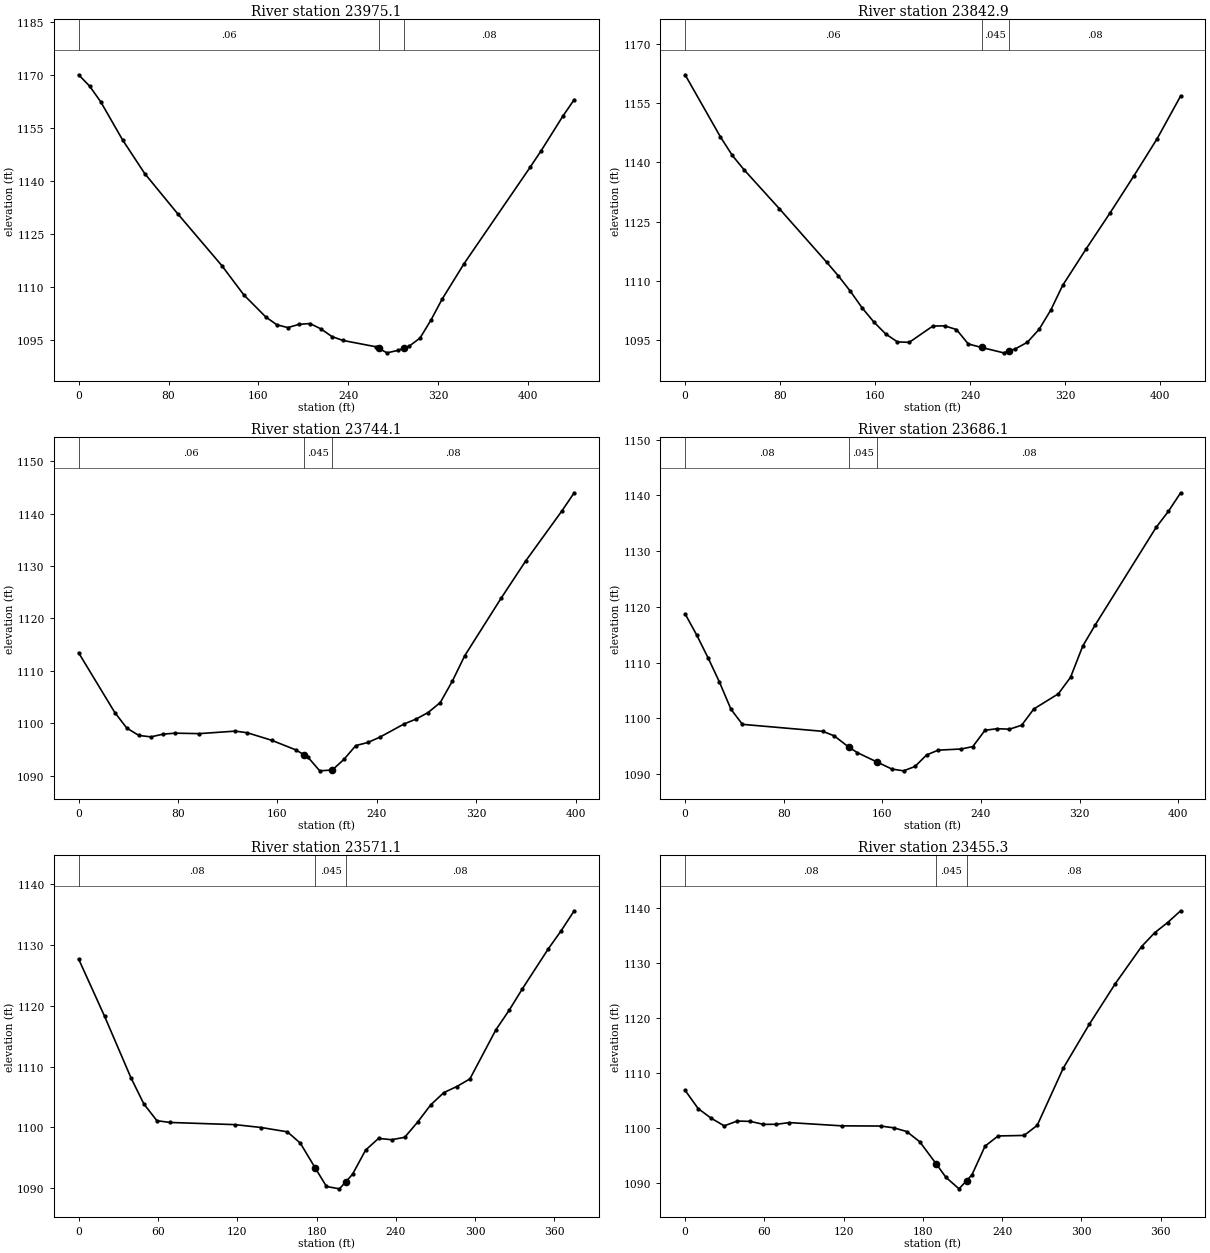
Type RM Length L Ch R = 1 ,23975.1 ,131,132.3,133.4
XS GIS Cut Line= 2
     1726757.217      412764.175     1727156.655      412951.196
#Sta/Elev= 30
       0 1169.99     9.8 1166.78    19.6 1162.39    39.2 1151.56    58.8 1142.11
    88.2 1130.74   127.4 1116.13     147 1107.86   166.6  1101.6   176.4 1099.41
   186.2 1098.62     196 1099.52   205.8 1099.77   215.6 1098.26   225.4 1096.09
   235.2 1094.99   264.6  1093.2     267 1092.78   274.4 1091.49   284.2 1092.18
     290 1092.87     294 1093.34   303.8 1095.65   313.6 1100.77   323.4 1106.61
     343 1116.66   401.8 1143.88   411.6 1148.54   431.2 1158.45     441 1162.95
#Mann= 3 , 0 , 0
       0     .06       0     267    .045       0     290     .08       0
Bank Sta=267,290
XS Rating Curve= 0 ,0
Exp/Cntr=0.3,0.1

Type RM Length L Ch R = 1 ,23842.9 ,63.1,98.8,128
XS GIS Cut Line= 2
     1726725.105      412875.805     1727094.918      413069.379
#Sta/Elev= 30
       0 1162.12    29.8 1146.41    39.8 1141.74    49.7 1138.12    79.5 1128.26
   119.3 1114.76   129.2 1111.28   139.1 1107.48   149.1 1103.25     159 1099.67
     169 1096.64   178.9 1094.64   188.8 1094.53   208.7 1098.65   218.6  1098.7
   228.6 1097.76   238.5 1094.13   249.7 1093.24   268.3 1091.88   272.7 1092.33
   278.3 1092.91   288.2 1094.53   298.2 1097.82   308.1 1102.73     318 1108.91
   337.9 1118.18   357.8 1127.16   377.7 1136.43   397.5 1145.92   417.4 1156.76
#Mann= 3 , 0 , 0
       0     .06       0   249.7    .045       0   272.7     .08       0
#XS Ineff= 2 , 0
          218.69  1098.6
Permanent Ineff=
       F       F
Bank Sta=249.7,272.7
XS Rating Curve= 0 ,0
Exp/Cntr=0.3,0.1

Type RM Length L Ch R = 1 ,23744.1 ,61.8,58,114.4
XS GIS Cut Line= 4
     1726792.098      412987.102     1726914.539       413017.32
      1726921.05      413172.268     1727033.244      413207.278
#Sta/Elev= 30
       0 1113.42    29.1 1102.03    38.8 1099.05    48.5 1097.65    58.2 1097.38
    67.9  1097.9    77.6 1098.09      97    1098   126.1 1098.48   135.8 1098.16
   155.2 1096.74   174.6 1094.91   181.1 1094.01   184.3 1093.56     194  1090.9
   204.1 1091.06   213.4 1093.07     223 1095.72   232.7 1096.31   242.4 1097.33
   261.8 1099.84   271.5 1100.78   281.2 1102.03     291 1103.94   300.8 1108.07
   310.6 1112.85     340 1123.87   359.6 1130.92   388.9 1140.52   398.7 1143.96
#Mann= 3 , 0 , 0
       0     .06       0   181.1    .045       0   204.1     .08       0
Bank Sta=181.1,204.1
XS Rating Curve= 0 ,0
Exp/Cntr=0.3,0.1

Type RM Length L Ch R = 1 ,23686.1 ,151.5,115,19.3
XS GIS Cut Line= 4
     1726761.716      413002.293     1726859.373      413032.675
     1726861.579      413163.731     1727023.777      413209.803
#Sta/Elev= 30
       0 1118.76     9.3 1115.01    18.6 1110.89    27.9 1106.51    37.2 1101.65
    46.5 1098.94   111.6 1097.69     121 1096.87   132.9 1094.83   139.7 1093.87
   155.9 1092.16   167.8 1090.92   177.2  1090.6   186.5 1091.38   195.9 1093.45
   205.3 1094.31     224 1094.52   233.4 1094.95   243.3 1097.88   253.2 1098.16
   263.1 1098.07     273 1098.78   282.9  1101.7   302.8 1104.42   312.7 1107.39
   322.6 1112.99   332.5  1116.7   382.1 1134.27     392 1137.13     402 1140.48
#Mann= 3 , 0 , 0
       0     .08       0   132.9    .045       0   155.9     .08       0
Bank Sta=132.9,155.9
XS Rating Curve= 0 ,0
Exp/Cntr=0.3,0.1

Type RM Length L Ch R = 1 ,23571.1 ,115.1,115.8,115.1
XS GIS Cut Line= 2
     1726651.948       413130.11     1727015.689      413221.045
#Sta/Elev= 30
       0  1127.7    19.7 1118.25    39.5 1108.21    49.3 1103.88    59.2 1101.11
    69.1 1100.82   118.4 1100.46   138.1 1099.99   157.9 1099.28   167.7 1097.42
   179.2 1093.26   187.5 1090.29   197.3  1089.9   202.2 1091.08   207.2 1092.29
   217.1 1096.27   226.9  1098.2   236.8 1097.98   246.7 1098.38   256.5 1100.89
   266.4 1103.72   276.3 1105.73   286.1 1106.73     296 1107.98   315.7 1116.07
   325.6 1119.24   335.5 1122.73   355.2 1129.34   365.1 1132.37   374.9 1135.64
#Mann= 3 , 0 , 0
       0     .08       0   179.2    .045       0   202.2     .08       0
Bank Sta=179.2,202.2
XS Rating Curve= 0 ,0
Exp/Cntr=0.3,0.1

Type RM Length L Ch R = 1 ,23455.3 ,226.6,223,217.1
XS GIS Cut Line= 2
     1726620.877      413238.121     1726984.103      413332.171
#Sta/Elev= 30
       0 1106.78     9.9 1103.46    19.8  1101.7    29.6 1100.32    39.5 1101.19
    49.4 1101.13    59.2 1100.59    69.1  1100.6      79 1100.91   118.5 1100.32
   148.1 1100.28     158 1099.96   167.8 1099.28   177.7 1097.41   190.2 1093.37
   197.5 1090.94   207.4 1088.85   213.2 1090.36   217.2  1091.4   227.1 1096.62
     237 1098.48   256.7 1098.57   266.6 1100.41   286.3 1110.81   306.1 1118.83
   325.8 1126.23   345.6 1132.95   355.5 1135.46   365.3 1137.32   375.2 1139.47
#Mann= 3 , 0 , 0
       0     .08       0   190.2    .045       0   213.2     .08       0
Bank Sta=190.2,213.2
XS Rating Curve= 0 ,0
Exp/Cntr=0.3,0.1

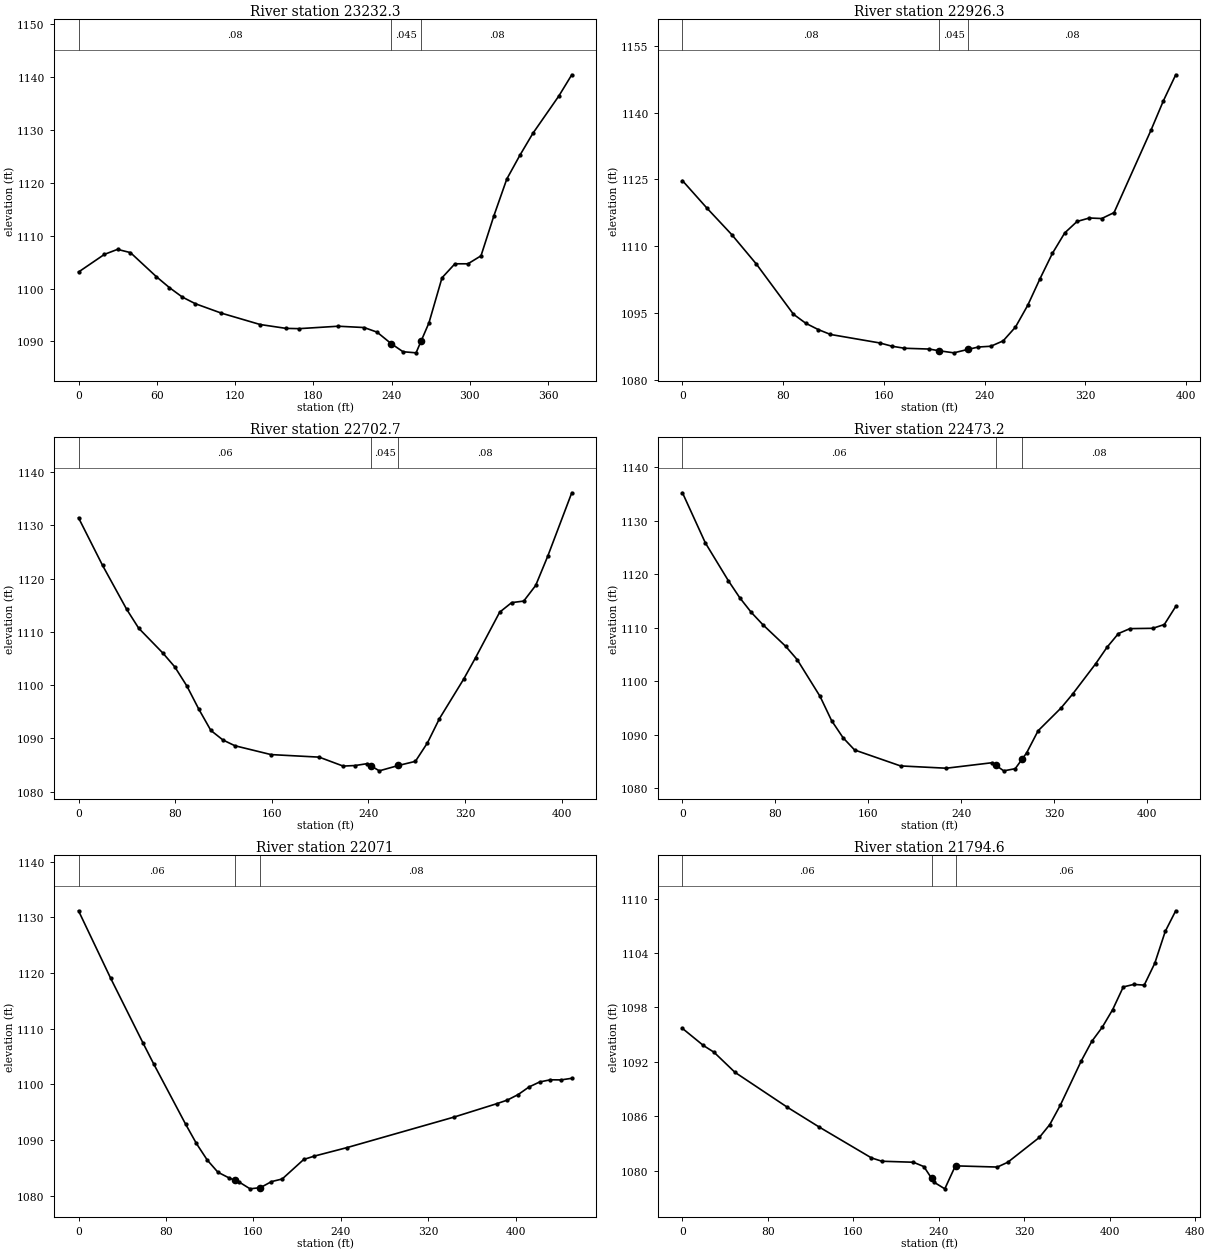
Type RM Length L Ch R = 1 ,23232.3 ,298.2,306,304.7
XS GIS Cut Line= 2
     1726571.139      413484.255     1726949.278      413476.445
#Sta/Elev= 30
       0 1103.12    19.9 1106.47    29.9 1107.41    39.8  1106.8    59.7 1102.24
    69.7 1100.17    79.6 1098.38    89.6 1097.12   109.5 1095.34   139.3 1093.18
   159.2 1092.45   169.2  1092.4   199.1 1092.86     219 1092.61   228.9 1091.74
   239.7 1089.57   248.8 1088.03   258.8 1087.82   262.7 1090.06   268.7  1093.5
   278.7 1102.03   288.6 1104.68   298.6 1104.68   308.6 1106.19   318.5 1113.78
   328.4 1120.74   338.4 1125.22   348.4 1129.39   368.3 1136.46   378.2 1140.47
#Mann= 3 , 0 , 0
       0     .08       0   239.7    .045       0   262.7     .08       0
Bank Sta=239.7,262.7
XS Rating Curve= 0 ,0
Exp/Cntr=0.3,0.1

Type RM Length L Ch R = 1 ,22926.3 ,224.5,223.6,214.6
XS GIS Cut Line= 2
     1726587.979       413774.08     1726978.512      413741.145
#Sta/Elev= 30
       0 1124.72    19.6  1118.5    39.2 1112.58    58.8 1105.95    88.2  1094.7
      98 1092.67   107.8 1091.27   117.6 1090.16   156.8 1088.25   166.6 1087.51
   176.4 1087.06     196 1086.88   203.9  1086.5   215.6 1086.03   226.9 1086.81
   235.2 1087.34     245 1087.51   254.8 1088.72   264.6 1091.83   274.3  1096.7
   284.1  1102.7   293.9 1108.37   303.7 1112.97   313.5 1115.55   323.3 1116.33
   333.1 1116.21   342.9 1117.54   372.3 1136.09   382.1 1142.66   391.9 1148.51
#Mann= 3 , 0 , 0
       0     .08       0   203.9    .045       0   226.9     .08       0
Bank Sta=203.9,226.9
XS Rating Curve= 0 ,0
Exp/Cntr=0.3,0.1

Type RM Length L Ch R = 1 ,22702.7 ,221.7,229.5,234.5
XS GIS Cut Line= 2
     1726601.192      414001.483     1727001.716      413920.975
#Sta/Elev= 30
       0 1131.41    19.9 1122.48    39.9 1114.23    49.8  1110.7    69.8 1106.04
    79.7 1103.44    89.7 1099.86    99.6 1095.51   109.6 1091.51   119.6 1089.72
   129.5 1088.64   159.4 1086.98   199.3  1086.5   219.2 1084.82   229.2 1084.93
   239.1 1085.28     242 1084.89   249.1 1083.93     265 1084.94     279 1085.71
     289 1089.19   298.9 1093.72   318.9 1101.11   328.8 1105.15   348.8  1113.7
   358.7 1115.49   368.7 1115.78   378.6 1118.71   388.6  1124.2   408.5  1136.1
#Mann= 3 , 0 , 0
       0     .06       0     242    .045       0     265     .08       0
Bank Sta=242,265
XS Rating Curve= 0 ,0
Exp/Cntr=0.3,0.1

Type RM Length L Ch R = 1 ,22473.2 ,355.3,402.2,353
XS GIS Cut Line= 2
     1726609.633      414146.758     1727033.566      414167.813
#Sta/Elev= 30
       0 1135.19    19.7 1125.82    39.5 1118.75    49.4 1115.54    59.2 1112.84
    69.1 1110.55    88.8  1106.5    98.7 1104.01   118.4 1097.13   128.3 1092.61
   138.2  1089.4   148.1 1087.12   187.6 1084.14     227 1083.71   266.5 1084.74
   269.5 1084.28   276.4 1083.22   286.3 1083.62   292.5 1085.49   296.1 1086.57
     306 1090.71   325.7 1094.96   335.6 1097.54   355.4  1103.2   365.2 1106.29
   375.1 1108.88     385  1109.8   404.7 1109.86   414.6 1110.57   424.4 1113.94
#Mann= 3 , 0 , 0
       0     .06       0   269.5    .045       0   292.5     .08       0
Bank Sta=269.5,292.5
XS Rating Curve= 0 ,0
Exp/Cntr=0.3,0.1

Type RM Length L Ch R = 1 ,22071   ,283.7,276.4,263.9
XS GIS Cut Line= 2
     1726624.727      414406.525     1727072.116      414466.577
#Sta/Elev= 27
       0  1131.2    29.4 1119.08    58.9 1107.48    68.7 1103.71    98.1 1092.81
   107.9 1089.37   117.8  1086.4   127.6  1084.2   137.4 1083.22   143.5 1082.72
   147.2 1082.42     157 1081.22   166.5 1081.44   176.6 1082.52   186.4 1082.99
   206.1  1086.5   215.9 1087.11   245.3 1088.61   343.5 1094.11   382.7 1096.52
   392.5 1097.18   402.3 1098.16   412.2 1099.52     422 1100.43   431.8 1100.82
   441.6  1100.8   451.4 1101.09
#Mann= 3 , 0 , 0
       0     .06       0   143.5    .045       0   166.5     .08       0
Bank Sta=143.5,166.5
XS Rating Curve= 0 ,0
Exp/Cntr=0.3,0.1

Type RM Length L Ch R = 1 ,21794.6 ,335.1,346.7,298.4
XS GIS Cut Line= 2
     1726641.858      414701.358     1727086.166      414575.464
#Sta/Elev= 30
       0 1095.69    19.6 1093.81    29.5 1093.07    49.1 1090.86    98.3    1087
   127.7 1084.85   176.9 1081.43   186.7 1081.06   216.2 1080.95     226 1080.47
   233.2 1079.19   235.8 1078.73   245.6 1078.02   255.5 1080.55   256.2 1080.55
   294.8 1080.42   304.6 1080.95   334.1 1083.68   343.9  1085.1   353.7 1087.22
   373.4 1092.12   383.2 1094.26     393 1095.82   402.8 1097.77   412.7 1100.26
   422.5 1100.54   432.3 1100.46   442.2 1102.87     452 1106.38   461.8 1108.65
#Mann= 3 , 0 , 0
       0     .06       0   233.2    .045       0   256.2     .06       0
Bank Sta=233.2,256.2
XS Rating Curve= 0 ,0
Exp/Cntr=0.3,0.1

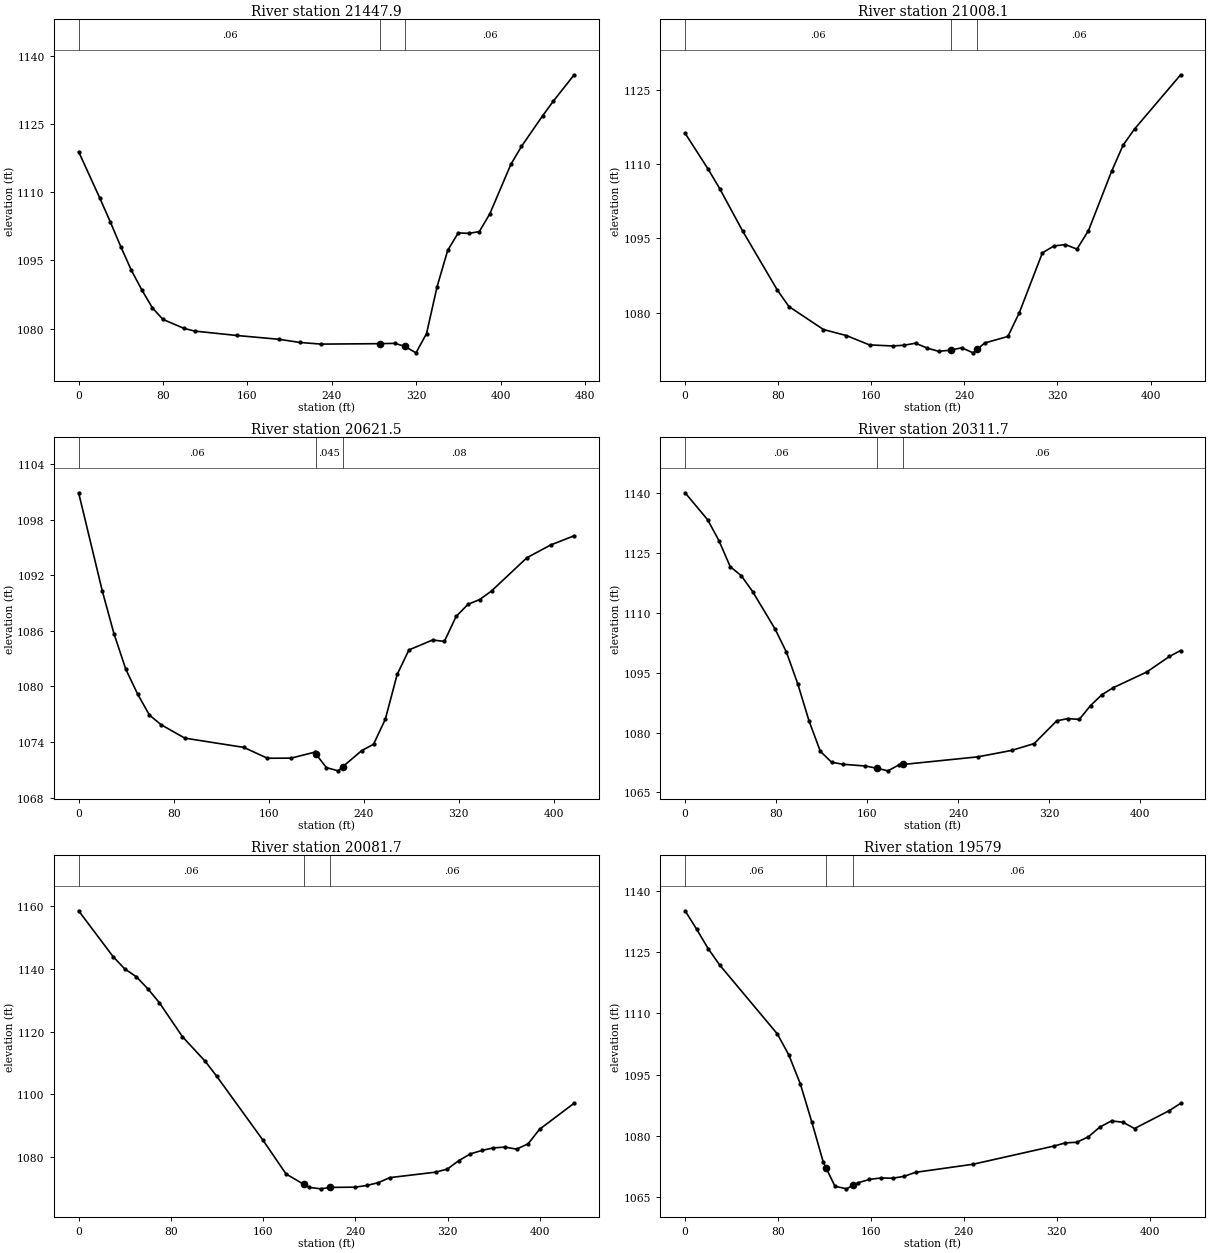
Type RM Length L Ch R = 1 ,21447.9 ,274.3,439.9,232.3
XS GIS Cut Line= 2
     1726652.411      414882.985     1727118.833      414828.631
#Sta/Elev= 30
       0 1118.92      20 1108.75      30 1103.48      40 1097.99      50 1092.81
      60 1088.47    69.9 1084.56    79.9 1082.01    99.9 1080.04   109.9 1079.45
   149.9 1078.48   189.8 1077.64   209.8 1076.94   229.8 1076.58     286 1076.68
   299.7 1076.75     309 1076.09   319.7 1074.66   329.7  1078.9   339.7 1089.22
   349.7 1097.18   359.7 1101.05   369.7 1100.95   379.7 1101.33   389.6 1105.22
   409.6 1116.12   419.6 1120.06   439.6 1126.78   449.6 1129.97   469.6 1135.84
#Mann= 3 , 0 , 0
       0     .06       0     286    .045       0     309     .06       0
Bank Sta=286,309
XS Rating Curve= 0 ,0
Exp/Cntr=0.3,0.1

Type RM Length L Ch R = 1 ,21008.1 ,283.3,386.6,232.4
XS GIS Cut Line= 2
     1726660.625      415024.341     1727084.442      415066.795
#Sta/Elev= 30
       0 1116.23    19.8 1108.99    29.7 1105.07    49.5 1096.48    79.2 1084.61
    89.2 1081.26   118.9 1076.62   138.7 1075.39   158.5 1073.51   178.3  1073.3
   188.2 1073.44   198.1 1073.86     208 1072.87   217.9 1072.22   228.3 1072.45
   237.7 1072.93   247.6 1071.91   251.3 1072.65   257.5  1073.9   277.4 1075.21
   287.3 1080.04   307.1  1092.1     317 1093.48   326.9 1093.76   336.8 1092.84
   346.7 1096.59   366.5 1108.51   376.4 1113.81   386.3 1117.09   425.9 1128.03
#Mann= 3 , 0 , 0
       0     .06       0   228.3    .045       0   251.3     .06       0
Bank Sta=228.3,251.3
XS Rating Curve= 0 ,0
Exp/Cntr=0.3,0.1

Type RM Length L Ch R = 1 ,20621.5 ,292.6,309.8,316.6
XS GIS Cut Line= 2
     1726685.567      415149.545     1727064.285      415324.481
#Sta/Elev= 30
       0  1100.9    19.9 1090.31    29.8 1085.67    39.7 1081.86    49.7 1079.17
    59.6 1076.91    69.5 1075.86    89.4 1074.42   139.1 1073.42   158.9 1072.25
   178.8 1072.26   198.6  1072.9   199.5 1072.75   208.6 1071.24   218.5 1070.89
   222.5 1071.35   238.4 1073.08   248.3 1073.76   258.2 1076.46   268.2  1081.3
   278.1 1083.94     298 1085.01   307.9 1084.86   317.8 1087.55   327.8 1088.86
   337.7 1089.38   347.6  1090.3   377.4 1093.89   397.3 1095.26   417.2 1096.26
#Mann= 3 , 0 , 0
       0     .06       0   199.5    .045       0   222.5     .08       0
Bank Sta=199.5,222.5
XS Rating Curve= 0 ,0
Exp/Cntr=0.3,0.1

Type RM Length L Ch R = 1 ,20311.7 ,225.8,230,272.1
XS GIS Cut Line= 2
     1726582.505      415314.801     1726965.916      415521.335
#Sta/Elev= 30
       0 1140.13    19.8 1133.37    29.7 1128.16    39.6 1121.64    49.5  1119.3
    59.4 1115.33    79.2 1105.92    89.1 1100.15      99 1092.25   108.9 1082.95
   118.8 1075.34   128.7 1072.58   138.6 1072.07   158.4 1071.63   168.7 1071.07
   178.2 1070.42   188.1 1071.94   191.7 1072.02   257.3 1073.93     287 1075.54
   306.8 1077.26   326.6 1082.96   336.5 1083.52   346.4 1083.31   356.3 1086.78
   366.2 1089.48   376.1 1091.24   405.8 1095.21   425.6 1099.09   435.5 1100.58
#Mann= 3 , 0 , 0
       0     .06       0   168.7    .045       0   191.7     .06       0
Bank Sta=168.7,191.7
XS Rating Curve= 0 ,0
Exp/Cntr=0.3,0.1

Type RM Length L Ch R = 1 ,20081.7 ,487.1,502.7,467.9
XS GIS Cut Line= 2
     1726455.984      415471.708     1726814.376       415708.92
#Sta/Elev= 30
       0 1158.49      30 1143.84      40 1139.99      50  1137.5      60 1133.66
      70 1129.24      90 1118.41   109.9 1110.52   119.9 1105.73   159.9 1085.44
   179.9 1074.69   195.3 1071.38   199.9 1070.43   209.9 1069.95   218.3  1070.4
   239.9 1070.49   249.9 1071.02   259.9 1071.92   269.9 1073.52   309.8 1075.27
   319.8 1076.24   329.8 1078.95   339.8 1081.08   349.8 1082.18   359.8    1083
   369.8 1083.24   379.8 1082.59   389.8 1084.27   399.8 1088.92   429.8 1097.22
#Mann= 3 , 0 , 0
       0     .06       0   195.3    .045       0   218.3     .06       0
Bank Sta=195.3,218.3
XS Rating Curve= 0 ,0
Exp/Cntr=0.3,0.1

Type RM Length L Ch R = 1 ,19579   ,296.9,297.9,299.1
XS GIS Cut Line= 2
     1726230.032      415757.854     1726540.191       416050.72
#Sta/Elev= 30
       0 1135.15     9.9 1130.66    19.8 1125.91    29.8 1121.86    79.4 1104.99
    89.3 1099.84    99.2 1092.75   109.1 1083.41     119 1073.54   121.5 1072.08
     129  1067.7   138.9 1067.05   144.5 1067.89   148.8 1068.53   158.7 1069.36
   168.6 1069.71   178.6 1069.65   188.5 1070.11   198.4 1071.09     248 1073.08
   317.4 1077.52   327.4  1078.3   337.3 1078.46   347.2  1079.8   357.1 1082.19
   367.1 1083.69     377 1083.36   386.9 1081.82   416.7 1086.19   426.6 1087.99
#Mann= 3 , 0 , 0
       0     .06       0   121.5    .045       0   144.5     .06       0
Bank Sta=121.5,144.5
XS Rating Curve= 0 ,0
Exp/Cntr=0.3,0.1

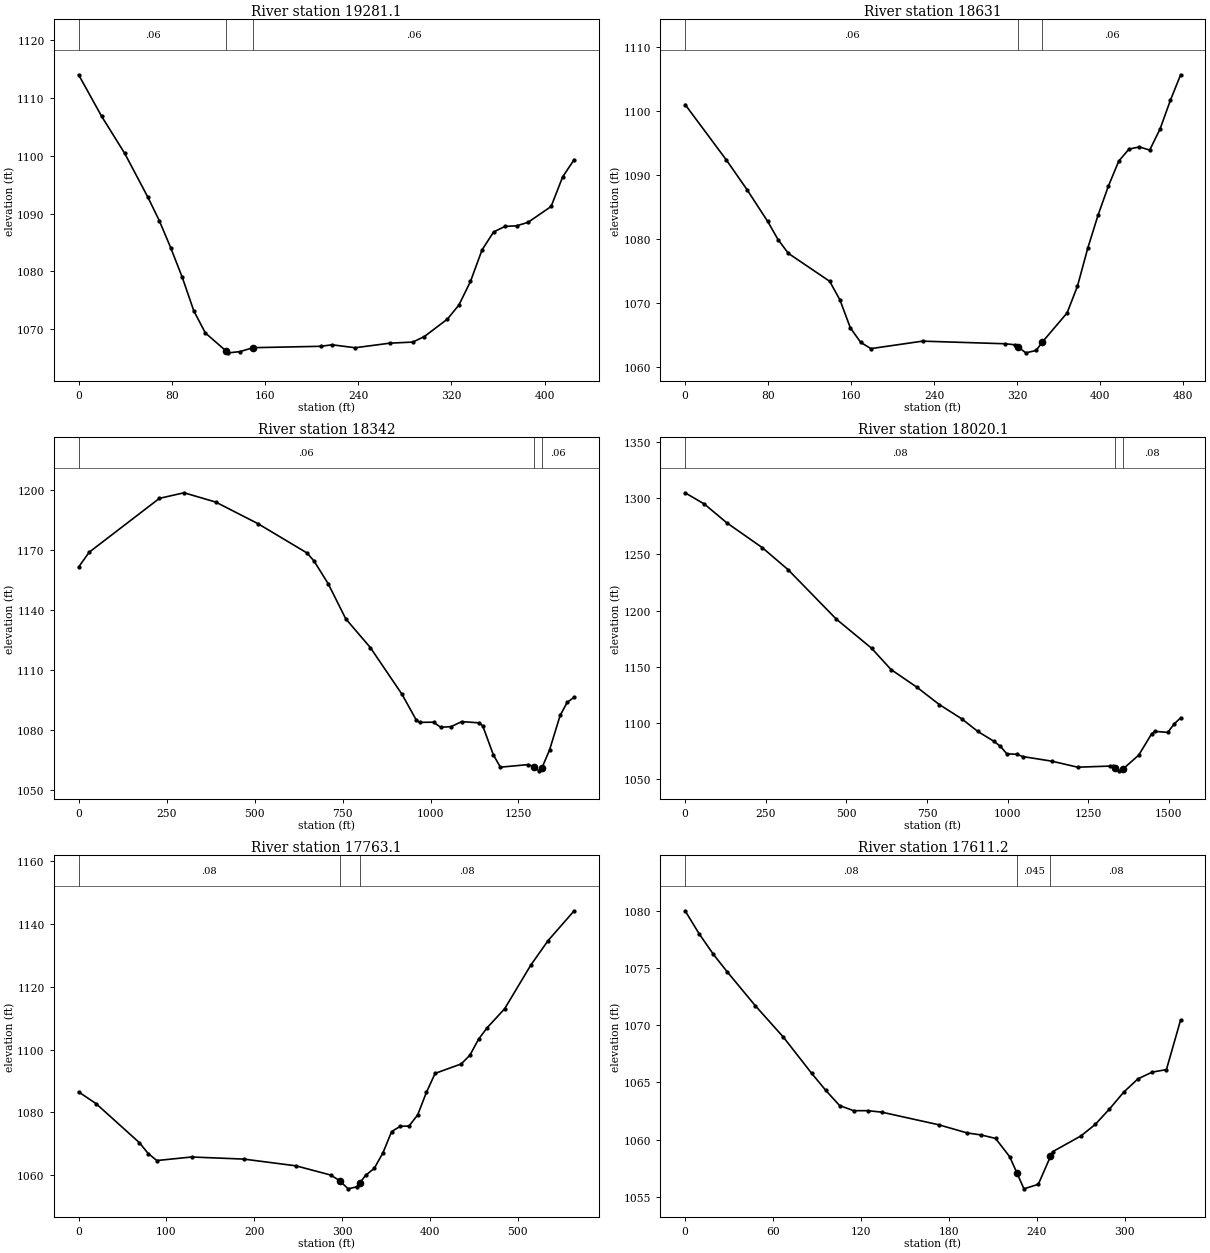
Type RM Length L Ch R = 1 ,19281.1 ,630.9,650.1,553.9
XS GIS Cut Line= 2
     1726058.477      415970.394     1726350.221      416279.994
#Sta/Elev= 30
       0 1113.98    19.8 1106.78    39.6 1100.38    59.4 1092.84    69.2 1088.79
    79.1 1084.06      89 1078.96    98.9 1073.17   108.8 1069.36   126.7 1066.23
   128.6 1065.93   138.5 1066.14   149.7 1066.82   207.8 1067.06   217.6 1067.32
   237.4 1066.81   267.1  1067.6   286.9 1067.79   296.8 1068.75   316.6 1071.76
   326.5 1074.21   336.4 1078.28   346.3 1083.71   356.2 1086.81     366 1087.78
   375.9 1087.88   385.8 1088.48   405.6 1091.22   415.5 1096.33   425.4 1099.32
#Mann= 3 , 0 , 0
       0     .06       0   126.7    .045       0   149.7     .06       0
Bank Sta=126.7,149.7
XS Rating Curve= 0 ,0
Exp/Cntr=0.3,0.1

Type RM Length L Ch R = 1 ,18631   ,297.4,289,297.3
XS GIS Cut Line= 2
     1725757.829      416247.697     1726108.599      416571.606
#Sta/Elev= 30
       0 1101.03    39.8 1092.34    59.7  1087.7    79.6 1082.73    89.5 1079.91
    99.5 1077.74   139.3 1073.37   149.2 1070.45   159.2 1066.09   169.1 1063.83
     179 1062.84   228.8 1064.01   308.4  1063.6   318.3 1063.43     321 1063.09
   328.2 1062.18   338.2 1062.55     344 1063.84     368 1068.42     378 1072.61
   387.9 1078.54   397.9 1083.75   407.8 1088.27   417.8 1092.18   427.7 1094.06
   437.7 1094.39   447.6  1093.9   457.6 1097.21   467.5 1101.68   477.4 1105.68
#Mann= 3 , 0 , 0
       0     .06       0     321    .045       0     344     .06       0
Bank Sta=321,344
XS Rating Curve= 0 ,0
Exp/Cntr=0.3,0.1

Type RM Length L Ch R = 1 ,18342   ,348.3,321.9,293.5
XS GIS Cut Line= 2
     1724718.047      416037.623     1725935.358      416745.771
#Sta/Elev= 30
       0 1161.57      30 1168.96   229.7  1195.9   299.6 1198.68   389.5 1194.04
   509.4 1183.26   649.2 1168.56   669.2  1164.5   709.2 1153.22   759.1 1135.66
     829 1121.28   918.9 1097.93   958.8 1085.26   968.8 1083.88  1008.8 1083.96
  1028.8 1081.41  1058.7 1081.74  1088.7 1084.25  1138.6 1083.63  1148.6 1082.05
  1178.6 1067.63  1198.6 1061.47  1278.5 1062.76  1293.4 1061.66  1308.4 1059.63
  1316.4 1060.98  1338.4 1070.12  1368.4 1087.32  1388.3 1093.83  1408.3 1096.47
#Mann= 3 , 0 , 0
       0     .06       0  1293.4    .045       0  1316.4     .06       0
Bank Sta=1293.4,1316.4
XS Rating Curve= 0 ,0
Exp/Cntr=0.3,0.1

Type RM Length L Ch R = 1 ,18020.1 ,255.4,257,258.8
XS GIS Cut Line= 2
     1724617.975      417632.104     1725970.591        416902.9
#Sta/Elev= 30
       0 1304.87    59.9  1294.8   129.7 1278.03   239.5 1255.98   319.3  1236.4
     469 1192.33   578.7 1166.31   638.6 1147.43   718.4 1131.79   788.3 1116.26
   858.1 1103.51     908 1092.26   957.9 1083.48   977.9 1079.03   997.8 1072.33
  1027.8 1072.01  1047.7 1069.91  1137.5 1065.82  1217.4 1060.47  1317.1 1061.45
  1327.1 1061.35  1333.9 1059.62  1347.1 1057.22  1356.9 1058.57  1406.9 1071.25
  1446.8 1090.23  1456.8 1092.38  1496.7 1091.45  1516.7 1098.98  1536.7 1104.42
#Mann= 3 , 0 , 0
       0     .08       0  1333.9    .045       0  1356.9     .08       0
Bank Sta=1333.9,1356.9
XS Rating Curve= 0 ,0
Exp/Cntr=0.3,0.1

Type RM Length L Ch R = 1 ,17763.1 ,151,151.9,152.8
XS GIS Cut Line= 2
     1725630.955      417353.962     1726142.727      417115.991
#Sta/Elev= 30
       0 1086.52    19.8 1082.81    69.3 1070.36    79.2 1066.94    89.1  1064.7
   128.7 1065.83   188.1 1065.16   247.5 1063.02   287.2 1060.08   297.3 1058.29
     307  1055.7   316.8 1056.34   320.3 1057.61   326.8 1059.98   336.7 1062.21
   346.6 1067.15   356.5 1073.92   366.4  1075.6   376.3 1075.66   386.2 1079.24
   396.1 1086.37     406 1092.42   435.7 1095.42   445.6 1098.19   455.5 1103.29
   465.4 1106.98   485.2 1112.97   514.9 1126.82   534.7 1134.66   564.4 1144.14
#Mann= 3 , 0 , 0
       0     .08       0   297.3    .045       0   320.3     .08       0
Bank Sta=297.3,320.3
XS Rating Curve= 0 ,0
Exp/Cntr=0.3,0.1

Type RM Length L Ch R = 1 ,17611.2 ,59.9,61,60.2
XS GIS Cut Line= 3
     1725735.641      417410.001     1725879.182      417402.102
     1726057.143      417323.915
#Sta/Elev= 30
       0 1080.05     9.6 1078.03    19.2 1076.25    28.8 1074.69    47.9 1071.73
    67.1 1068.97    86.3 1065.81    95.8 1064.34   105.4 1062.98     115 1062.53
   124.6 1062.53   134.2  1062.4   172.9  1061.3   192.4 1060.58   202.1  1060.4
   211.8  1060.1   221.5 1058.49   226.3  1057.1   231.2 1055.68     241 1056.08
   249.3 1058.52   250.7 1058.93   270.1 1060.32   279.8 1061.32   289.5 1062.67
   299.3 1064.16     309 1065.32   318.7 1065.91   328.4 1066.13   338.1 1070.49
#Mann= 3 , 0 , 0
       0     .08       0   226.3    .045       0   249.3     .08       0
Bank Sta=226.3,249.3
XS Rating Curve= 0 ,0
Exp/Cntr=0.3,0.1

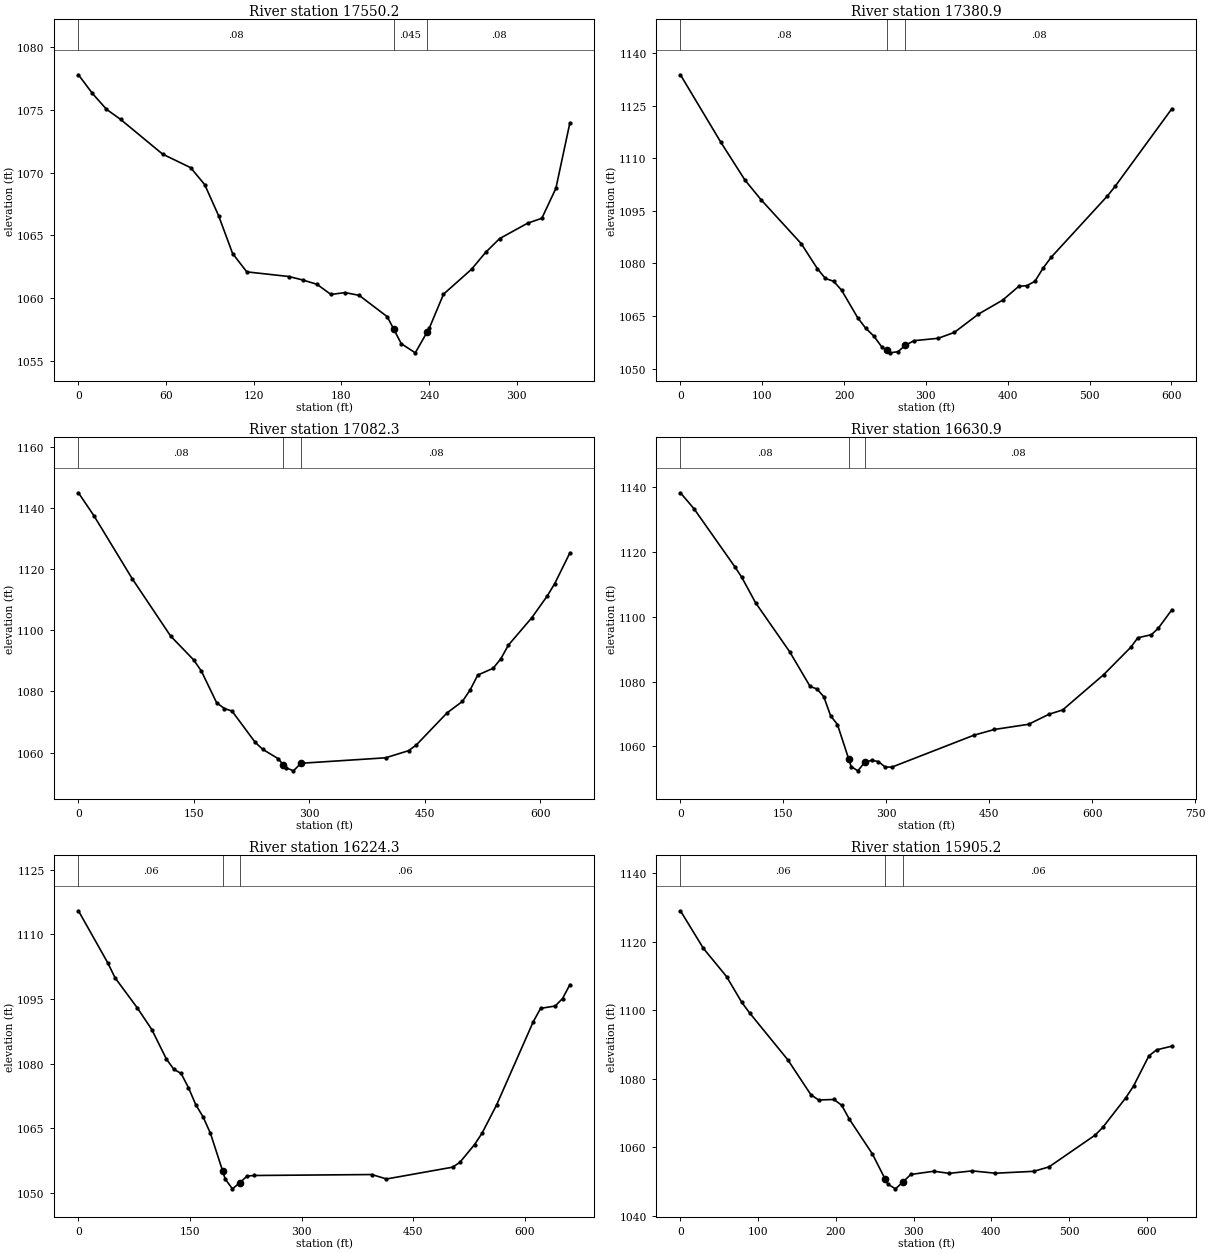
Type RM Length L Ch R = 1 ,17550.2 ,180.4,169.3,158.8
XS GIS Cut Line= 3
     1725790.249      417449.726     1725895.638      417455.291
     1726108.187      417365.451
#Sta/Elev= 30
       0 1077.79     9.6  1076.3    19.2 1075.04    28.8 1074.24    57.6 1071.47
    76.8 1070.39    86.4 1069.04    95.9 1066.57   105.5 1063.55   115.2 1062.09
     144 1061.72   153.6 1061.44   163.2  1061.1   172.8 1060.29   182.4 1060.44
   192.1 1060.22   211.3 1058.52   215.6 1057.56   220.9 1056.37   230.5 1055.64
   238.6  1057.3   240.1 1057.61   249.8 1060.31     269  1062.3   278.6 1063.64
   288.2 1064.74   307.4 1065.97   317.1 1066.36   326.7 1068.74   336.3 1073.97
#Mann= 3 , 0 , 0
       0     .08       0   215.6    .045       0   238.6     .08       0
Bank Sta=215.6,238.6
XS Rating Curve= 0 ,0
Exp/Cntr=0.3,0.1

Type RM Length L Ch R = 1 ,17380.9 ,295.9,298.6,301.4
XS GIS Cut Line= 2
     1725892.305      417733.089     1726335.487      417327.649
#Sta/Elev= 30
       0 1133.79    49.2 1114.62    78.8 1103.79    98.5 1098.17   147.7 1085.62
   167.4  1078.5   177.2  1075.7   187.1 1074.92   196.9 1072.39   216.6 1064.53
   226.5  1061.5   236.3 1059.31   246.2 1056.15     252 1055.17     256  1054.5
   265.9 1054.83     275 1056.68   285.6 1057.97   315.1 1058.65   334.8 1060.33
   364.3 1065.55   393.9 1069.54   413.6 1073.48   423.4 1073.65   433.3  1074.9
   443.1  1078.6     453 1081.72   521.9 1099.24   531.7  1102.1   600.7 1124.13
#Mann= 3 , 0 , 0
       0     .08       0     252    .045       0     275     .08       0
Bank Sta=252,275
XS Rating Curve= 0 ,0
Exp/Cntr=0.3,0.1

Type RM Length L Ch R = 1 ,17082.3 ,453.9,451.3,448.8
XS GIS Cut Line= 2
     1726054.967      417967.163     1726545.881       417558.67
#Sta/Elev= 30
       0 1144.92      20 1137.48    69.8 1116.88   119.8  1098.1   149.7 1090.32
   159.7 1086.68   179.6  1076.3   189.6 1074.43   199.6 1073.59   229.5 1063.43
   239.5 1061.08   259.4 1058.06   266.1 1056.08   269.4 1055.11   279.4 1054.06
   289.1 1056.53   399.2 1058.32   429.1 1060.66   439.1 1062.53     479 1073.01
   498.9 1076.74   508.9 1080.47   518.9 1085.36   538.8 1087.56   548.8 1090.66
   558.8 1095.18   588.8    1104   608.7 1111.03   618.7 1115.16   638.6 1125.29
#Mann= 3 , 0 , 0
       0     .08       0   266.1    .045       0   289.1     .08       0
Bank Sta=266.1,289.1
XS Rating Curve= 0 ,0
Exp/Cntr=0.3,0.1

Type RM Length L Ch R = 1 ,16630.9 ,421.6,406.6,391.5
XS GIS Cut Line= 2
     1726326.844      418338.358     1726832.408      417831.076
#Sta/Elev= 30
       0 1138.31    19.9 1133.35    79.6 1115.36    89.5 1112.16   109.4 1104.38
   159.2  1089.2     189 1078.48   198.9 1077.72   208.9 1075.32   218.8 1069.45
   228.8 1066.73   245.3 1056.02   248.7 1053.75   258.6 1052.42   268.3 1055.01
   278.5 1055.67   288.5 1055.29   298.4 1053.58   308.4 1053.59   427.7 1063.43
   457.6  1065.2   507.3  1066.8   537.1  1069.9     557 1071.23   616.7 1082.12
   656.5 1090.64   666.5 1093.52   686.4 1094.48   696.3 1096.46   716.2 1102.19
#Mann= 3 , 0 , 0
       0     .08       0   245.3    .045       0   268.3     .08       0
Bank Sta=245.3,268.3
XS Rating Curve= 0 ,0
Exp/Cntr=0.3,0.1

Type RM Length L Ch R = 1 ,16224.3 ,316.4,319.1,321.9
XS GIS Cut Line= 2
     1726808.618      418551.235     1726951.825      417906.458
#Sta/Elev= 30
       0 1115.49    39.4  1103.4    49.3  1099.9    78.9 1092.99    98.6  1087.9
   118.3 1081.02   128.2 1078.68     138  1077.7   147.9  1074.4   157.7 1070.44
   167.6 1067.59   177.4  1063.8   193.7 1055.11   197.2 1053.19     207  1050.9
   216.7 1052.29   226.7 1053.88   236.6    1054   394.3 1054.22     414 1053.19
   502.8 1055.93   512.6 1057.05   532.3 1061.17   542.2 1063.76   561.9 1070.36
   611.2  1089.7   621.1 1092.82   640.8 1093.37   650.6 1095.11   660.5 1098.34
#Mann= 3 , 0 , 0
       0     .06       0   193.7    .045       0   216.7     .06       0
Bank Sta=193.7,216.7
XS Rating Curve= 0 ,0
Exp/Cntr=0.3,0.1

Type RM Length L Ch R = 1 ,15905.2 ,232.8,247.1,261.4
XS GIS Cut Line= 2
     1727080.485      418661.281     1727280.018      418061.167
#Sta/Elev= 30
       0 1129.08    29.6  1118.1    59.3 1109.89      79 1102.34    88.9  1099.3
   138.3 1085.54     168 1075.34   177.9 1073.86   197.6    1074   207.5 1072.31
   217.4 1068.24     247 1058.11   263.5 1050.72   266.8 1049.32   276.7 1047.92
   286.5 1049.95   296.4 1052.11   326.1 1053.06   345.8 1052.44   375.5 1053.16
   405.1 1052.48   454.6 1053.03   474.3 1054.33   533.6  1063.6   543.5 1065.87
   573.1 1074.51     583 1077.91   602.8 1086.73   612.6 1088.48   632.4 1089.57
#Mann= 3 , 0 , 0
       0     .06       0   263.5    .045       0   286.5     .06       0
Bank Sta=263.5,286.5
XS Rating Curve= 0 ,0
Exp/Cntr=0.3,0.1