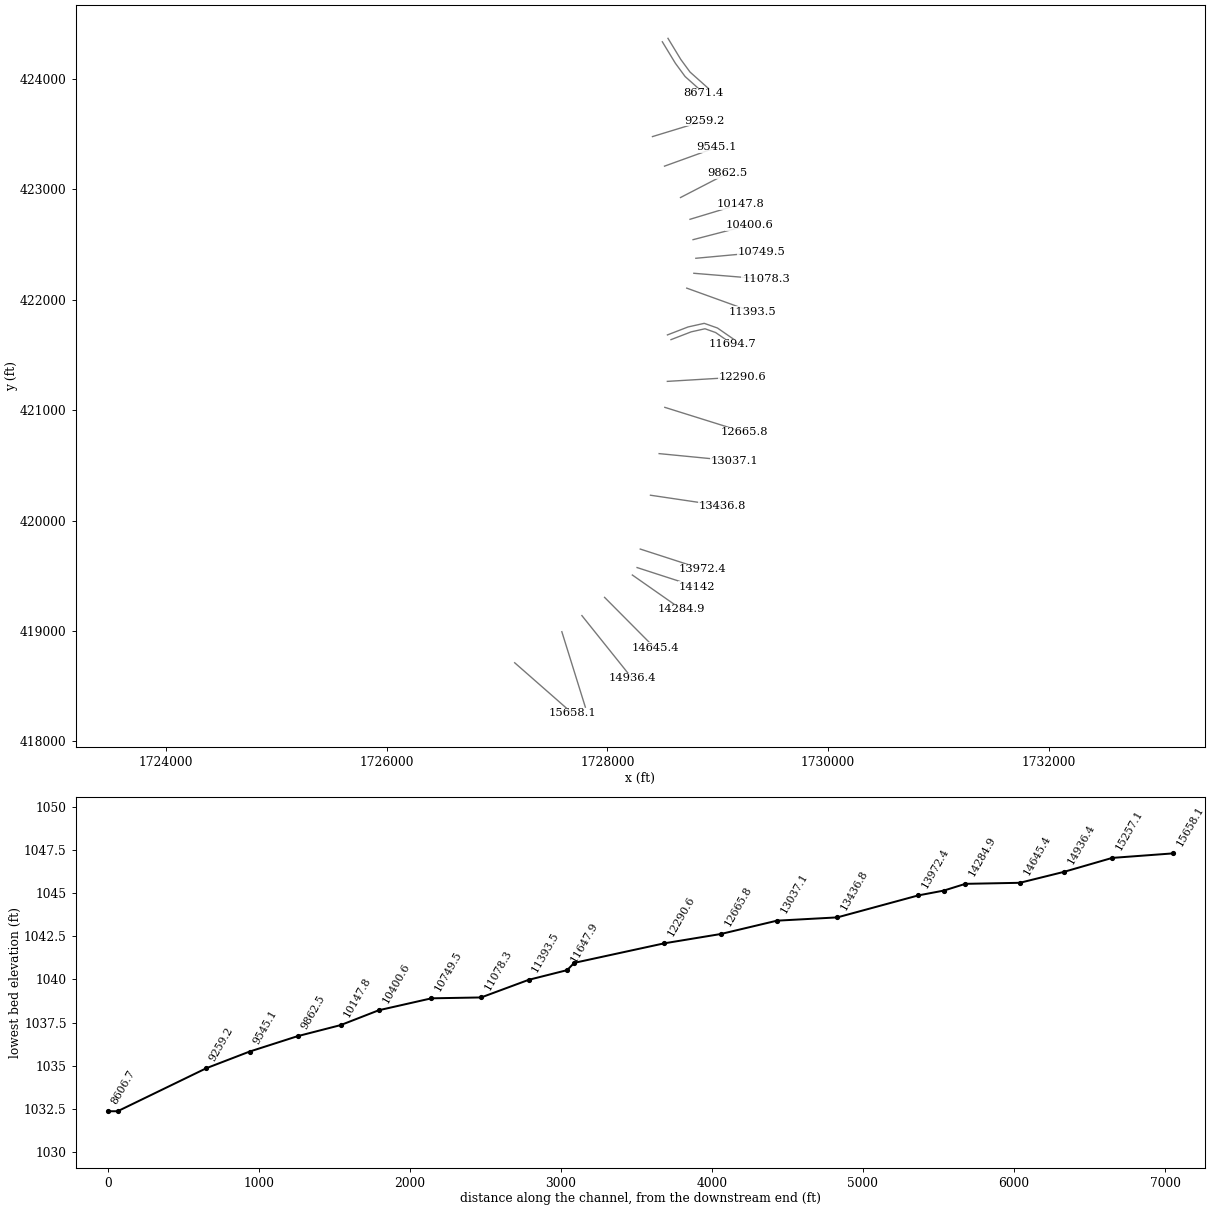
HEC-RAS study SouthFork.prj: SouthFork

--- SouthFork.g01 (geometry) --- (continued)

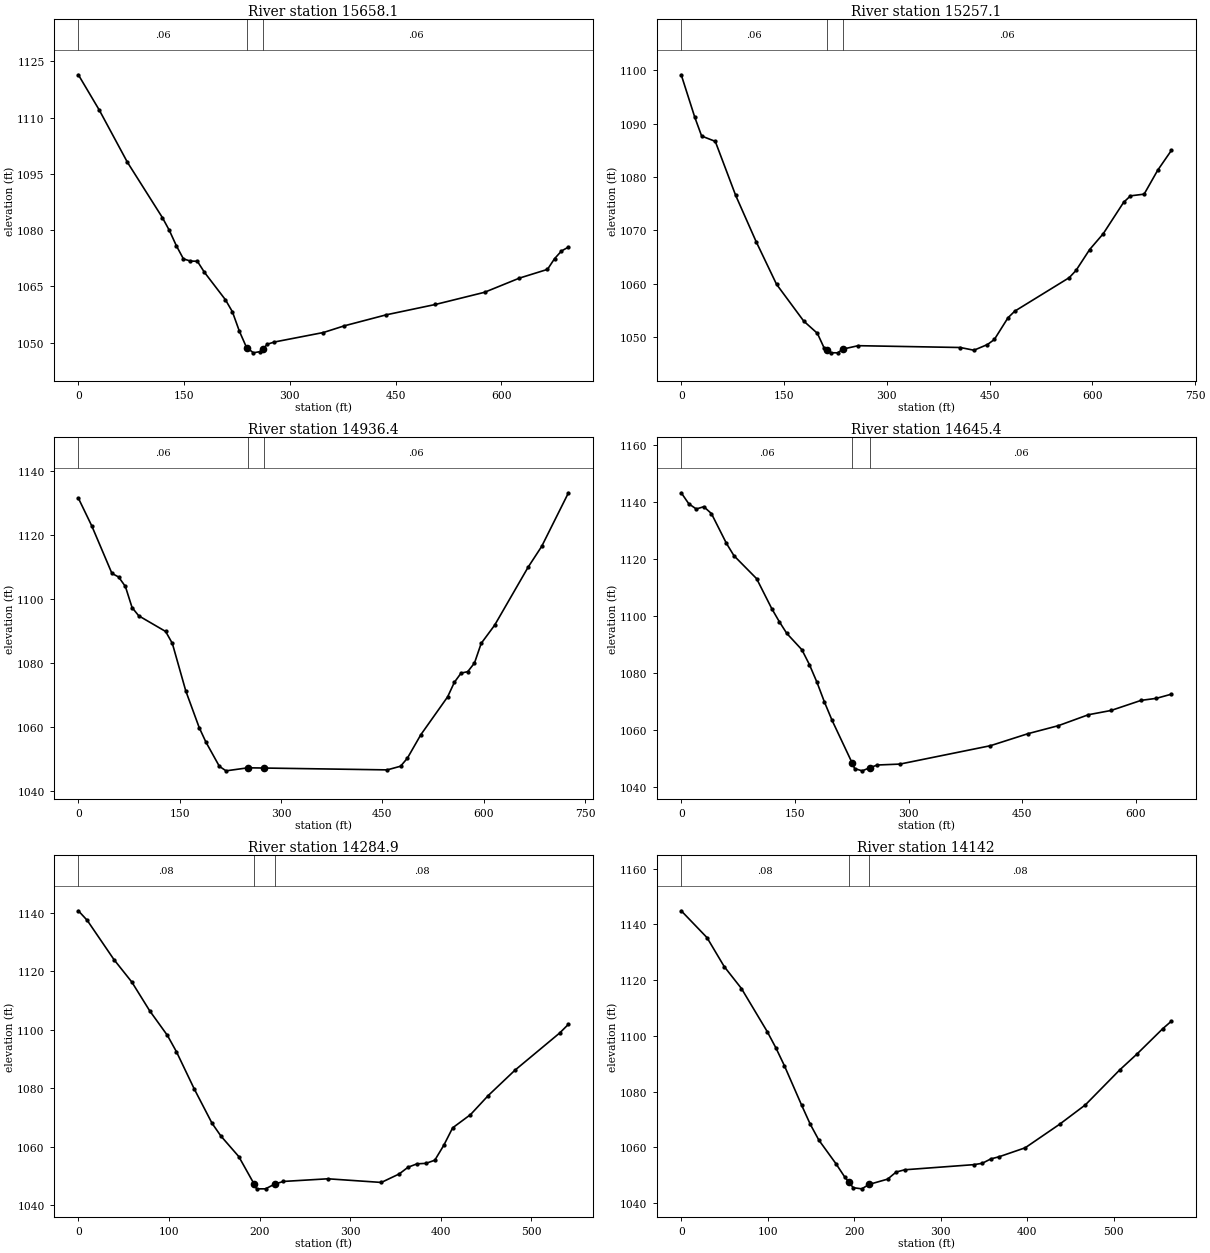
Type RM Length L Ch R = 1 ,15658.1 ,415.6,401.1,386.4
XS GIS Cut Line= 2
     1727160.323      418712.606     1727683.323      418254.532
#Sta/Elev= 30
       0 1121.43    29.8 1111.98    69.5 1098.13   119.2 1083.35   129.1 1079.92
     139 1075.85     149 1072.35   158.9 1071.76   168.8 1071.71   178.8 1068.77
   208.6 1061.45   218.5 1058.24   228.4 1053.06   238.4 1048.78   239.2 1048.66
   248.3 1047.29   258.2 1047.64   262.2 1048.42   268.2  1049.6   278.1 1050.18
   347.6 1052.71   377.4  1054.5     437 1057.44   506.5 1060.19   576.1 1063.43
   625.7 1067.22   665.4 1069.54   675.4 1072.38   685.3 1074.45   695.2 1075.49
#Mann= 3 , 0 , 0
       0     .06       0   239.2    .045       0   262.2     .06       0
Bank Sta=239.2,262.2
XS Rating Curve= 0 ,0
Exp/Cntr=0.3,0.1

Type RM Length L Ch R = 1 ,15257.1 ,310.6,320.7,330.5
XS GIS Cut Line= 2
     1727587.459      418993.537     1727800.505      418310.716
#Sta/Elev= 30
       0 1099.14    19.9 1091.14    29.8 1087.66    49.7 1086.66    79.5 1076.53
   109.3 1067.88   139.1 1059.88   178.8 1052.98   198.7 1050.69   208.6 1047.94
   212.5 1047.59   218.6 1047.05   228.5 1047.03   235.5 1047.72   258.3 1048.37
   407.3 1048.03   427.2 1047.52     447 1048.59     457 1049.53   476.9  1053.6
   486.8 1054.84   566.3 1061.12   576.2 1062.47   596.1 1066.39   615.9 1069.35
   645.7 1075.24   655.7 1076.45   675.6 1076.77   695.4 1081.25   715.3 1084.95
#Mann= 3 , 0 , 0
       0     .06       0   212.5    .045       0   235.5     .06       0
Bank Sta=212.5,235.5
XS Rating Curve= 0 ,0
Exp/Cntr=0.3,0.1

Type RM Length L Ch R = 1 ,14936.4 ,288.1,291,293.8
XS GIS Cut Line= 2
     1727769.074      419139.425     1728222.817      418573.324
#Sta/Elev= 30
       0 1131.57    19.9 1122.86    49.7 1108.02    59.6 1106.89    69.6 1103.93
    79.5 1097.33    89.4 1094.74   129.2 1089.84   139.1 1086.12     159 1071.24
   178.9 1059.74   188.8 1055.23   208.7 1047.64   218.6 1046.22   251.1 1047.17
   274.1  1047.1   457.2 1046.52     477 1047.67     487 1050.17   506.9 1057.51
   546.6 1069.37   556.6 1073.93   566.5  1076.8   576.4 1077.27   586.4 1079.98
   596.3 1086.11   616.2  1091.8   665.9 1110.01   685.8 1116.45   725.5 1133.25
#Mann= 3 , 0 , 0
       0     .06       0   251.1    .045       0   274.1     .06       0
Bank Sta=251.1,274.1
XS Rating Curve= 0 ,0
Exp/Cntr=0.3,0.1

Type RM Length L Ch R = 1 ,14645.4 ,355.7,360.4,365.2
XS GIS Cut Line= 2
     1727974.496      419304.436      1728430.59      418846.044
#Sta/Elev= 30
       0 1143.31      10 1139.44    19.9 1137.61    29.8 1138.42    39.8 1136.02
    59.7 1125.51    69.6 1121.19    99.5 1113.12   119.4 1102.62   129.3 1098.06
   139.3 1093.88   159.2 1088.15   169.1 1082.94   179.1 1076.71     189 1069.74
     199 1063.35   225.5 1048.37   228.8 1046.38   238.8 1045.59   248.5 1046.66
   258.7 1047.64   288.5 1047.96   407.9 1054.42   457.6 1058.66   497.4 1061.45
   537.2 1065.31     567  1066.8   606.8 1070.36   626.7 1071.06   646.6 1072.52
#Mann= 3 , 0 , 0
       0     .06       0   225.5    .045       0   248.5     .06       0
Bank Sta=225.5,248.5
XS Rating Curve= 0 ,0
Exp/Cntr=0.3,0.1

Type RM Length L Ch R = 1 ,14284.9 ,135.1,142.9,150.8
XS GIS Cut Line= 2
     1728226.217      419506.638     1728669.599      419196.929
#Sta/Elev= 30
       0  1140.7     9.8 1137.42    39.3 1123.99      59 1116.31    78.7 1106.47
    98.3 1098.03   108.2 1092.48   127.8 1079.77   147.5 1067.98   157.3  1063.6
     177 1056.58   193.7 1047.31   196.7 1045.53   206.5 1045.53   216.7 1047.16
   226.2 1048.06   275.3 1048.97   334.3 1047.72     354 1050.62   363.8 1052.93
   373.7 1054.09   383.5 1054.25   393.3 1055.32   403.2 1060.42     413 1066.41
   432.7 1070.93   452.3 1077.47   481.8 1086.15     531 1098.84   540.8 1101.86
#Mann= 3 , 0 , 0
       0     .08       0   193.7    .045       0   216.7     .08       0
Bank Sta=193.7,216.7
XS Rating Curve= 0 ,0
Exp/Cntr=0.3,0.1

Type RM Length L Ch R = 1 ,14142   ,169.5,169.6,169.5
XS GIS Cut Line= 2
     1728268.872      419574.243     1728807.788      419399.802
#Sta/Elev= 30
       0 1144.88    29.8 1135.25    49.7 1124.86    69.6    1117    99.4 1101.54
   109.3 1095.77   119.2 1089.34   139.1 1075.18   149.1 1068.33     159 1062.65
   178.9 1054.12   188.8 1049.46     194 1047.43   198.8 1045.55   208.7 1045.14
     217 1046.72   238.5 1048.62   248.4 1051.17   258.4 1051.98   337.9 1053.81
   347.8 1054.29   357.8 1055.87   367.7 1056.68   397.5 1059.86   437.3 1068.31
   467.1 1075.27   506.8 1087.81   526.7  1093.5   556.5 1102.59   566.4 1105.26
#Mann= 3 , 0 , 0
       0     .08       0     194    .045       0     217     .08       0
Bank Sta=194,217
XS Rating Curve= 0 ,0
Exp/Cntr=0.3,0.1

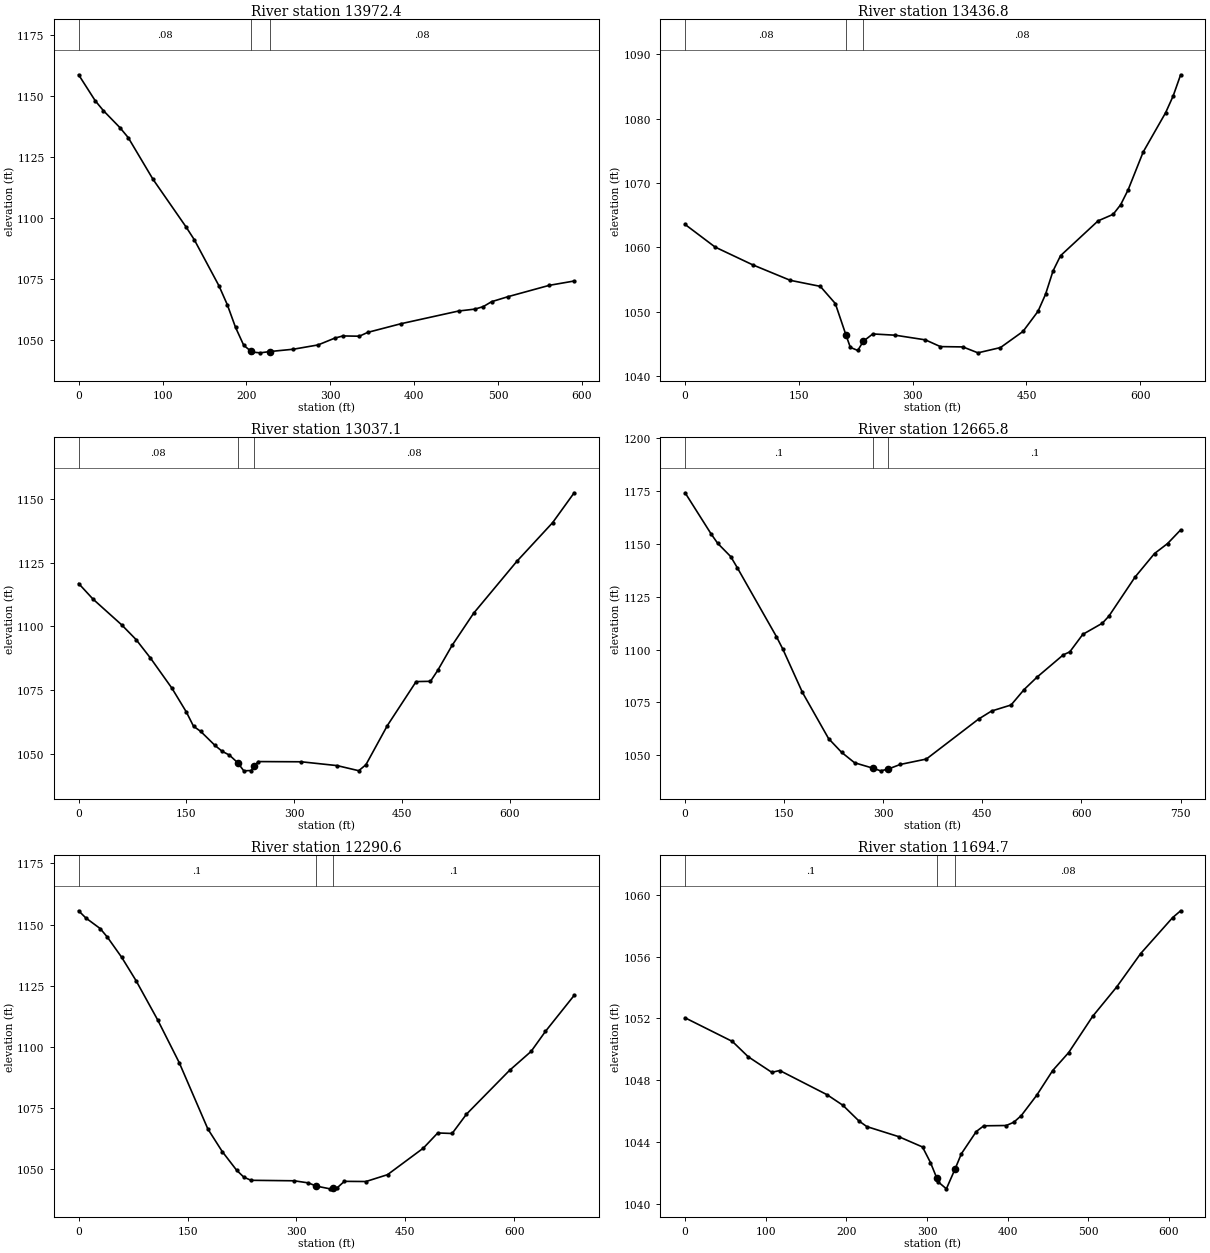
Type RM Length L Ch R = 1 ,13972.4 ,531.2,535.6,540
XS GIS Cut Line= 2
     1728297.851      419741.678     1728859.703      419559.813
#Sta/Elev= 30
       0  1158.7    19.7 1148.11    29.5 1144.03    49.2 1137.07    59.1 1132.98
    88.6 1115.93     128 1096.42   137.8  1091.2   167.3 1072.27   177.2 1064.56
     187 1055.29   196.8 1047.92   205.1 1045.61   206.7 1045.17   216.5 1044.86
   228.1  1045.4   255.9 1046.34   285.4  1048.1   305.1 1050.86     315 1051.78
   334.6 1051.67   344.5 1053.23   383.9 1056.76   452.8 1061.98   472.4 1062.77
   482.3 1063.79   492.1 1065.79   511.8 1067.86     561  1072.5   590.6 1074.27
#Mann= 3 , 0 , 0
       0     .08       0   205.1    .045       0   228.1     .08       0
Bank Sta=205.1,228.1
XS Rating Curve= 0 ,0
Exp/Cntr=0.3,0.1

Type RM Length L Ch R = 1 ,13436.8 ,398.3,399.7,401
XS GIS Cut Line= 2
     1728390.317      420228.952     1729036.503       420133.22
#Sta/Elev= 30
       0 1063.56    39.6 1060.04    89.1 1057.28   138.6 1054.87   178.2 1053.93
     198 1051.26     212 1046.38   217.8 1044.44   227.6 1043.96     235  1045.4
   247.4 1046.53   277.1 1046.33   316.7 1045.61   336.5 1044.56   366.2 1044.51
     386 1043.59   415.7 1044.41   445.4 1046.92   465.2 1050.05   475.1 1052.69
     485 1056.33   494.9  1058.7   544.4 1064.12   564.2 1065.13   574.1 1066.62
     584 1068.95   603.8 1074.82   633.4 1080.94   643.3 1083.53   653.2 1086.84
#Mann= 3 , 0 , 0
       0     .08       0     212    .045       0     235     .08       0
Bank Sta=212,235
XS Rating Curve= 0 ,0
Exp/Cntr=0.3,0.1

Type RM Length L Ch R = 1 ,13037.1 ,376.6,371.2,365.6
XS GIS Cut Line= 2
     1728468.793      420605.462     1729155.306      420538.611
#Sta/Elev= 30
       0 1116.84      20 1110.73      60 1100.61      80 1094.85     100 1087.61
     130 1075.74     150 1066.44   159.9  1060.9   169.9 1058.86   189.9 1053.34
   199.9 1051.04   209.9 1049.57   221.5 1046.56   229.9  1043.4   239.9 1043.53
   244.5 1045.14   249.9 1047.03   309.9 1046.95   359.9 1045.45   389.9 1043.45
   399.9 1045.79   429.8 1061.17   469.8 1078.39   489.8  1078.5   499.8 1082.75
   519.8 1092.55   549.8 1105.17   609.8 1125.47   659.8  1140.7   689.8 1152.41
#Mann= 3 , 0 , 0
       0     .08       0   221.5    .045       0   244.5     .08       0
Bank Sta=221.5,244.5
XS Rating Curve= 0 ,0
Exp/Cntr=0.3,0.1

Type RM Length L Ch R = 1 ,12665.8 ,350.3,375.2,385.1
XS GIS Cut Line= 2
     1728520.328      421024.183      1729236.29      420800.279
#Sta/Elev= 30
       0 1174.28    39.5 1154.74    49.4 1150.33    69.1 1144.06      79 1138.81
   138.2 1106.22   148.1 1100.17   177.7 1079.73   217.2 1057.91   236.9  1051.4
   256.6 1046.45   284.5 1043.87   296.1 1042.63   307.5 1043.48   325.7 1045.65
   365.2 1048.21   444.2 1067.12   463.9 1070.94   493.5 1073.81   513.3 1081.14
     533 1087.05   572.5 1097.54   582.4 1098.96   602.1 1107.25   631.7 1112.53
   641.6 1115.88   681.1 1134.34   710.7 1145.53   730.4 1150.24   750.2  1156.7
#Mann= 3 , 0 , 0
       0      .1       0   284.5    .045       0   307.5      .1       0
Bank Sta=284.5,307.5
XS Rating Curve= 0 ,0
Exp/Cntr=0.3,0.1

Type RM Length L Ch R = 1 ,12290.6 ,606.2,596,584.7
XS GIS Cut Line= 2
     1728543.188      421259.326      1729224.51      421299.993
#Sta/Elev= 30
       0 1155.67     9.9 1152.74    29.7  1148.4    39.6  1144.9    59.4 1136.62
    79.1 1127.12   108.8 1111.13   138.5 1093.67     178 1066.53   197.8 1057.32
   217.6  1049.7   227.5 1046.87   237.4 1045.58   296.8 1045.38   316.5 1044.51
   326.9 1043.24   346.2 1042.09   349.9 1042.25   356.1 1042.52     366 1045.15
   395.7 1045.08   425.4 1047.87   474.8 1058.73   494.6 1064.92   514.4  1064.7
   534.2  1072.6   593.5 1090.49   623.2 1098.23     643 1106.43   682.5 1121.12
#Mann= 3 , 0 , 0
       0      .1       0   326.9    .045       0   349.9      .1       0
Bank Sta=326.9,349.9
XS Rating Curve= 0 ,0
Exp/Cntr=0.3,0.1

Type RM Length L Ch R = 1 ,11694.7 ,50.9,46.8,46.2
XS GIS Cut Line= 5
     1728576.215       421637.04     1728758.833      421707.478
     1728884.128      421735.456     1728980.409      421701.406
     1729135.431      421594.182
#Sta/Elev= 30
       0 1052.03    58.7  1050.5    78.3 1049.51   107.6  1048.5   117.4 1048.62
   176.2 1047.05   195.7 1046.37   215.5 1045.36   225.4 1044.99   264.9 1044.34
   294.5 1043.67   304.4 1042.66   312.1 1041.67   314.2  1041.4   324.1 1040.96
   335.1 1042.27   342.7 1043.23   361.2 1044.67   370.5 1045.04   398.4 1045.06
   407.7 1045.27     417  1045.7   436.2 1047.02     456 1048.62   475.8 1049.78
   505.6 1052.13   535.4 1054.03   565.1 1056.19   604.8 1058.52   614.7 1058.96
#Mann= 3 , 0 , 0
       0      .1       0   312.1    .045       0   335.1     .08       0
Bank Sta=312.1,335.1
XS Rating Curve= 0 ,0
Exp/Cntr=0.3,0.1

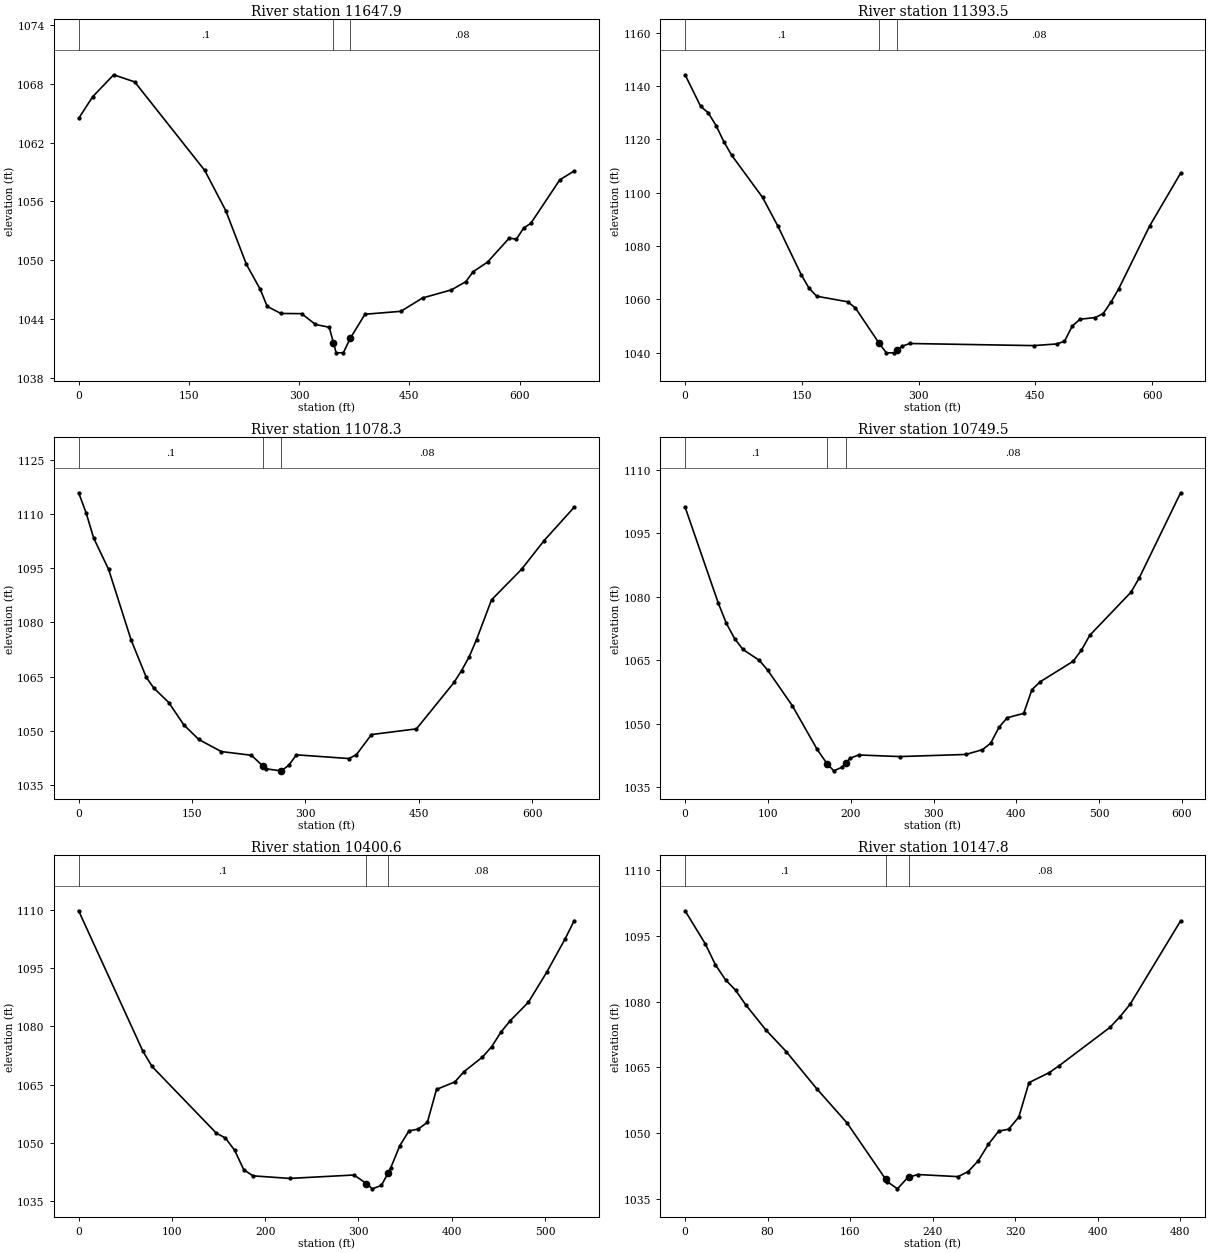
Type RM Length L Ch R = 1 ,11647.9 ,265.2,254.4,256.9
XS GIS Cut Line= 5
     1728544.069      421679.827     1728730.848      421751.871
     1728877.324      421784.579     1728997.404      421742.111
     1729159.008      421630.335
#Sta/Elev= 30
       0 1064.47    19.1 1066.69    47.7 1068.93    76.3  1068.2   171.6 1059.16
   200.2 1055.05   228.3 1049.56   247.1 1047.02   256.5 1045.28   275.2 1044.56
   303.4 1044.54   322.1 1043.44   340.9 1043.15   346.6 1041.57   350.3 1040.54
   360.1 1040.55   369.6 1042.03   389.5 1044.48   438.4 1044.78   467.8 1046.14
   507.1 1046.97   526.8 1047.81   536.6 1048.82   556.2  1049.8   585.7 1052.25
   595.5 1052.15   605.4 1053.28   615.2 1053.77   654.5  1058.2   674.1 1059.11
#Mann= 3 , 0 , 0
       0      .1       0   346.6    .045       0   369.6     .08       0
Bank Sta=346.6,369.6
XS Rating Curve= 0 ,0
Exp/Cntr=0.3,0.1

Type RM Length L Ch R = 1 ,11393.5 ,301.5,315.2,322.4
XS GIS Cut Line= 2
     1728718.766      422103.257     1729317.592      421887.201
#Sta/Elev= 30
       0 1144.18    19.9  1132.4    29.8 1129.89    39.8 1125.15    49.7 1119.16
    59.7 1114.09    99.5 1098.23   119.4 1087.35   149.2 1069.25   159.2 1064.21
   169.1 1061.19   208.9 1059.11   218.8 1056.79   249.3 1043.56   258.6 1039.98
   268.6 1039.98   272.3 1040.88   278.5  1042.4   288.5 1043.48   447.6 1042.69
   477.5 1043.31   487.4 1044.32   497.4 1050.02   507.3 1052.57   527.2 1053.22
   537.1 1054.71   547.1 1058.96     557 1063.95   596.8 1087.53   636.6 1107.32
#Mann= 3 , 0 , 0
       0      .1       0   249.3    .045       0   272.3     .08       0
Bank Sta=249.3,272.3
XS Rating Curve= 0 ,0
Exp/Cntr=0.3,0.1

Type RM Length L Ch R = 1 ,11078.3 ,328.6,328.8,321.9
XS GIS Cut Line= 2
     1728783.164      422237.654     1729436.325      422184.034
#Sta/Elev= 30
       0 1115.85     9.9  1110.3    19.9 1103.32    39.7 1094.64    69.5  1075.1
    89.4 1064.85    99.3 1061.88   119.2 1057.85     139 1051.71   158.9 1047.63
   188.7 1044.29   228.4 1043.27     244 1040.25   248.2 1039.51     267 1038.97
   268.1 1038.96     278  1040.5     288 1043.39   357.5 1042.36   367.4 1043.43
   387.3 1048.99   446.8 1050.57   496.5  1063.4   506.4 1066.67   516.3  1070.4
   526.3 1075.27   546.1 1086.25   585.8 1094.69   615.6 1102.62   655.4 1111.85
#Mann= 3 , 0 , 0
       0      .1       0     244    .045       0     267     .08       0
Bank Sta=244,267
XS Rating Curve= 0 ,0
Exp/Cntr=0.3,0.1

Type RM Length L Ch R = 1 ,10749.5 ,344.7,348.9,352.7
XS GIS Cut Line= 2
     1728801.313      422373.435     1729397.039      422428.413
#Sta/Elev= 30
       0 1101.19    39.9 1078.61    49.8 1073.75    59.8 1070.13    69.8 1067.58
    89.7 1064.98    99.7 1062.69   129.6 1054.24   159.5 1043.96   171.2 1040.64
   179.5 1038.91   189.4 1039.76   194.2 1040.78   199.4 1041.88   209.4 1042.66
   259.2 1042.28     339 1042.78     359 1043.91   368.9 1045.42   378.9 1049.16
   388.9 1051.45   408.8 1052.48   418.8  1058.1   428.8 1059.95   468.6 1064.79
   478.6 1067.44   488.6 1070.92   538.4  1081.1   548.4  1084.5   598.3 1104.57
#Mann= 3 , 0 , 0
       0      .1       0   171.2    .045       0   194.2     .08       0
Bank Sta=171.2,194.2
XS Rating Curve= 0 ,0
Exp/Cntr=0.3,0.1

Type RM Length L Ch R = 1 ,10400.6 ,252.1,252.8,252.9
XS GIS Cut Line= 2
     1728776.059        422541.8     1729290.365      422675.226
#Sta/Elev= 30
       0 1109.73    68.9 1073.62    78.7 1069.69   147.6 1052.55   157.4 1051.29
   167.3 1048.12   177.1 1043.12     187 1041.56   226.3  1040.9   295.2 1041.78
   308.6 1039.57   314.9 1038.22   324.7 1039.12   331.6 1042.23   334.5 1043.54
   344.4 1049.34   354.2 1053.11   364.1  1053.6   373.9 1055.32   383.7 1063.79
   403.4 1065.72   413.3 1068.38   432.9  1072.1   442.8 1074.75   452.6 1078.46
   462.5 1081.41   482.1 1086.17   501.8  1093.9   521.5 1102.46   531.3 1107.17
#Mann= 3 , 0 , 0
       0      .1       0   308.6    .045       0   331.6     .08       0
Bank Sta=308.6,331.6
XS Rating Curve= 0 ,0
Exp/Cntr=0.3,0.1

Type RM Length L Ch R = 1 ,10147.8 ,281.3,285.3,289.1
XS GIS Cut Line= 2
     1728748.393       422726.24     1729208.304      422865.094
#Sta/Elev= 30
       0 1100.68    19.6 1093.14    29.4 1088.39    39.2 1084.96      49 1082.59
    58.8 1079.26    78.4 1073.52      98 1068.63   127.5 1060.19   156.9  1052.4
   194.3  1039.6   196.1 1038.99   205.9 1037.36   215.7 1039.91   217.3 1040.03
   225.5 1040.62   264.7 1040.14   274.5  1041.3   284.3 1043.78   294.1 1047.54
   303.9 1050.48   313.7 1050.95   323.5 1053.71   333.4 1061.55     353 1063.82
   362.8 1065.43   411.8 1074.11   421.6 1076.56   431.4 1079.39   480.4  1098.4
#Mann= 3 , 0 , 0
       0      .1       0   194.3    .045       0   217.3     .08       0
Bank Sta=194.3,217.3
XS Rating Curve= 0 ,0
Exp/Cntr=0.3,0.1

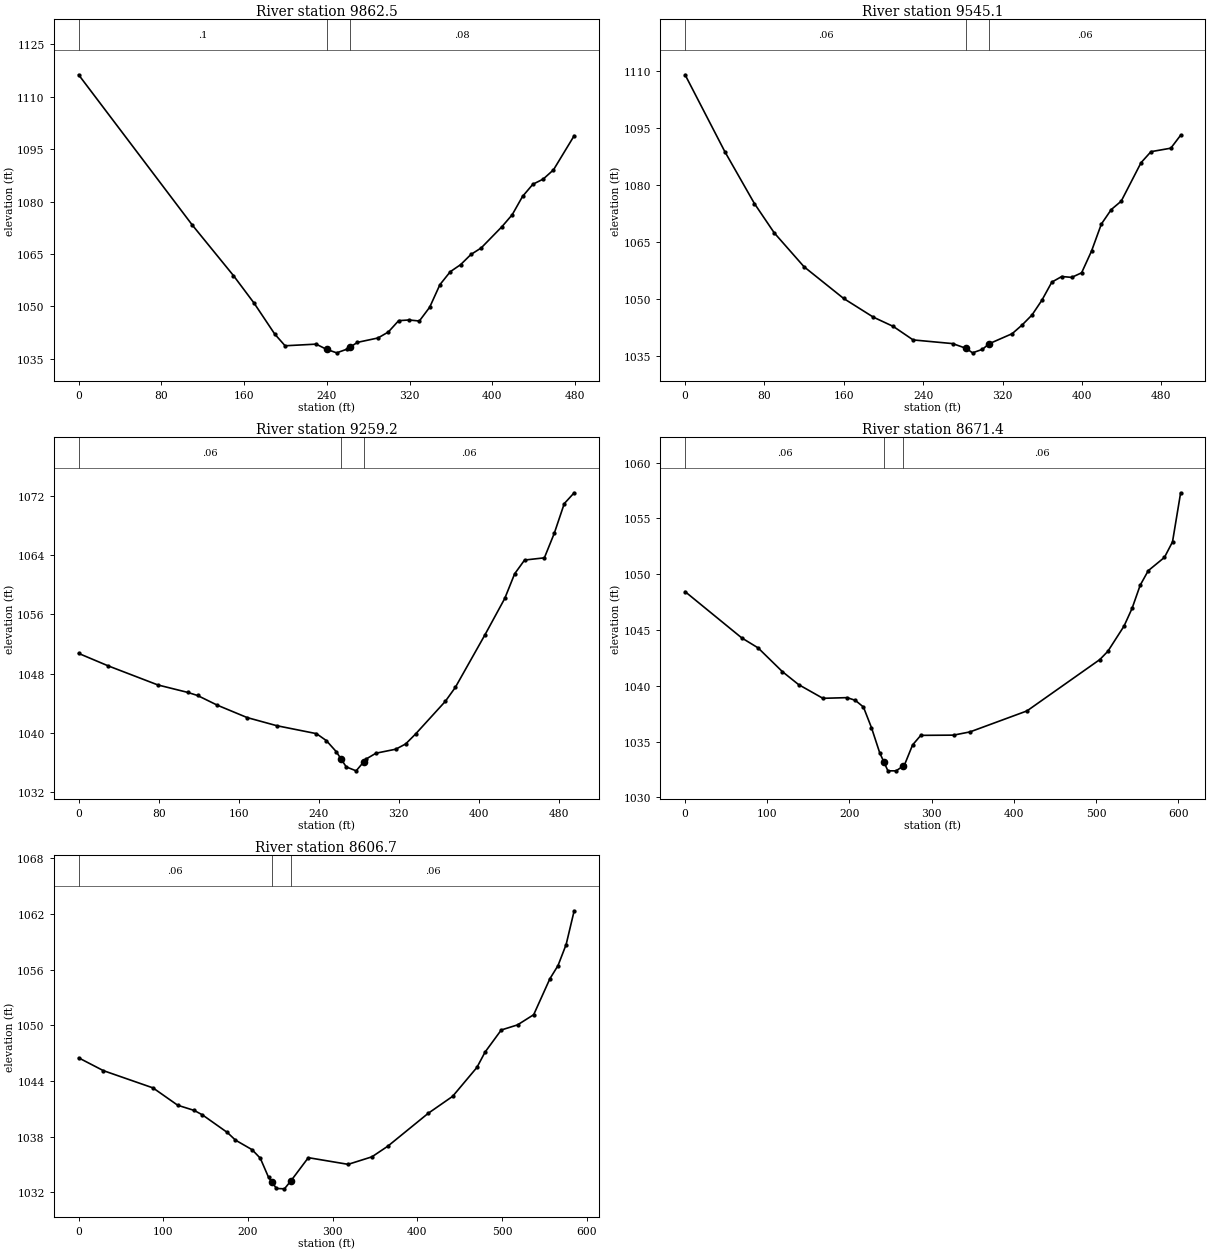
Type RM Length L Ch R = 1 ,9862.5  ,319.4,317.4,314.7
XS GIS Cut Line= 2
       1728662.5      422923.256     1729088.087      423143.243
#Sta/Elev= 30
       0 1116.24   109.8  1073.3   149.7 1058.81   169.7 1050.91   189.6 1042.09
   199.6 1038.74   229.6 1039.21   239.8 1037.71   249.5 1036.72   259.5 1037.78
   262.8 1038.42   269.5 1039.71   289.4 1040.97   299.4 1042.67   309.4 1045.92
   319.4 1046.12   329.4 1045.82   339.4 1049.76   349.3 1056.22   359.3 1059.92
   369.3 1061.94   379.3 1064.85   389.2 1066.72   409.2 1072.78   419.2 1076.22
   429.2 1081.46   439.2 1084.94   449.1  1086.4   459.1 1089.05   479.1 1098.81
#Mann= 3 , 0 , 0
       0      .1       0   239.8    .045       0   262.8     .08       0
Bank Sta=239.8,262.8
XS Rating Curve= 0 ,0
Exp/Cntr=0.3,0.1

Type RM Length L Ch R = 1 ,9545.1  ,286.9,285.9,284.3
XS GIS Cut Line= 2
     1728517.355      423207.236     1728987.122      423376.848
#Sta/Elev= 30
       0 1109.02      40 1088.81    69.9 1075.11    89.9 1067.39   119.9 1058.48
   159.8 1050.14   189.8 1045.21   209.8 1042.78   229.8 1039.23   269.7 1038.26
   283.2 1037.01   289.7 1035.83   299.7 1036.76   306.2  1038.2   329.6 1040.87
   339.6 1043.15   349.6 1045.79   359.6 1049.69   369.6 1054.45   379.6 1055.92
   389.6 1055.69   399.6  1056.9   409.6 1062.62   419.5 1069.73   429.5 1073.55
   439.5 1075.75   459.5 1085.88   469.5 1088.78   489.5  1089.7   499.4 1093.11
#Mann= 3 , 0 , 0
       0     .06       0   283.2    .045       0   306.2     .06       0
Bank Sta=283.2,306.2
XS Rating Curve= 0 ,0
Exp/Cntr=0.3,0.1

Type RM Length L Ch R = 1 ,9259.2  ,621.7,587.8,551.1
XS GIS Cut Line= 2
     1728408.444      423474.717     1728882.353      423619.254
#Sta/Elev= 30
       0 1050.72    29.7 1049.03    79.3 1046.46     109 1045.46   118.9 1045.04
   138.7 1043.73   168.5 1042.06   198.2 1040.96   237.8 1039.89   247.7 1038.95
   257.6 1037.46   262.3 1036.49   267.6  1035.4   277.5 1034.87   285.3 1036.12
   287.4 1036.46   297.3 1037.25   317.1 1037.79     327  1038.5   336.9 1039.84
   366.6 1044.24   376.6 1046.12   406.3 1053.23   426.1 1058.14     436 1061.47
   445.9 1063.32   465.7 1063.62   475.6 1066.93   485.6 1070.94   495.5  1072.4
#Mann= 3 , 0 , 0
       0     .06       0   262.3    .045       0   285.3     .06       0
Bank Sta=262.3,285.3
XS Rating Curve= 0 ,0
Exp/Cntr=0.3,0.1

Type RM Length L Ch R = 1 ,8671.4  ,64.1,64.7,67.9
XS GIS Cut Line= 4
     1728497.624      424332.862     1728615.486      424139.045
     1728704.063      424018.257     1728873.096      423867.713
#Sta/Elev= 30
       0 1048.44      69 1044.29    88.8  1043.4   118.4 1041.27   138.1 1040.11
   167.7 1038.88   197.2 1038.94   207.1  1038.7     217  1038.1   226.8 1036.25
   236.8    1034   242.1 1033.14   246.8 1032.38   256.8 1032.38   265.1  1032.8
   266.8 1032.88   276.8  1034.7   286.8 1035.56   326.7 1035.58   346.7 1035.87
     416 1037.75   504.6 1042.35   514.4 1043.09   534.1 1045.35   543.9 1046.94
   553.8 1049.02   563.6 1050.32   583.3 1051.51   593.1  1052.9     603  1057.3
#Mann= 3 , 0 , 0
       0     .06       0   242.1    .045       0   265.1     .06       0
Bank Sta=242.1,265.1
XS Rating Curve= 0 ,0
Exp/Cntr=0.3,0.1

Type RM Length L Ch R = 1 ,8606.7  ,124.1,135.2,143.8
XS GIS Cut Line= 4
      1728548.89      424364.036     1728665.403      424172.436
     1728748.701      424058.849     1728913.001      423912.519
#Sta/Elev= 30
       0  1046.5    29.2 1045.12    87.8 1043.26     117 1041.39   136.5 1040.83
   146.2 1040.35   175.5 1038.46   185.2 1037.63   204.8  1036.6   214.5 1035.68
   224.2 1033.63   227.9 1033.15   233.6 1032.42     243 1032.38   250.9 1033.27
   271.2 1035.74   318.2 1035.02   346.3 1035.83   365.1 1036.98   412.9 1040.53
   441.6 1042.35   470.3 1045.47   479.9 1047.12     499  1049.5   518.2 1050.05
   537.3 1051.15   556.4 1055.02     566 1056.44   575.6 1058.71   585.1 1062.35
#Mann= 3 , 0 , 0
       0     .06       0   227.9    .045       0   250.9     .06       0
Bank Sta=227.9,250.9
XS Rating Curve= 0 ,0
Exp/Cntr=0.3,0.1