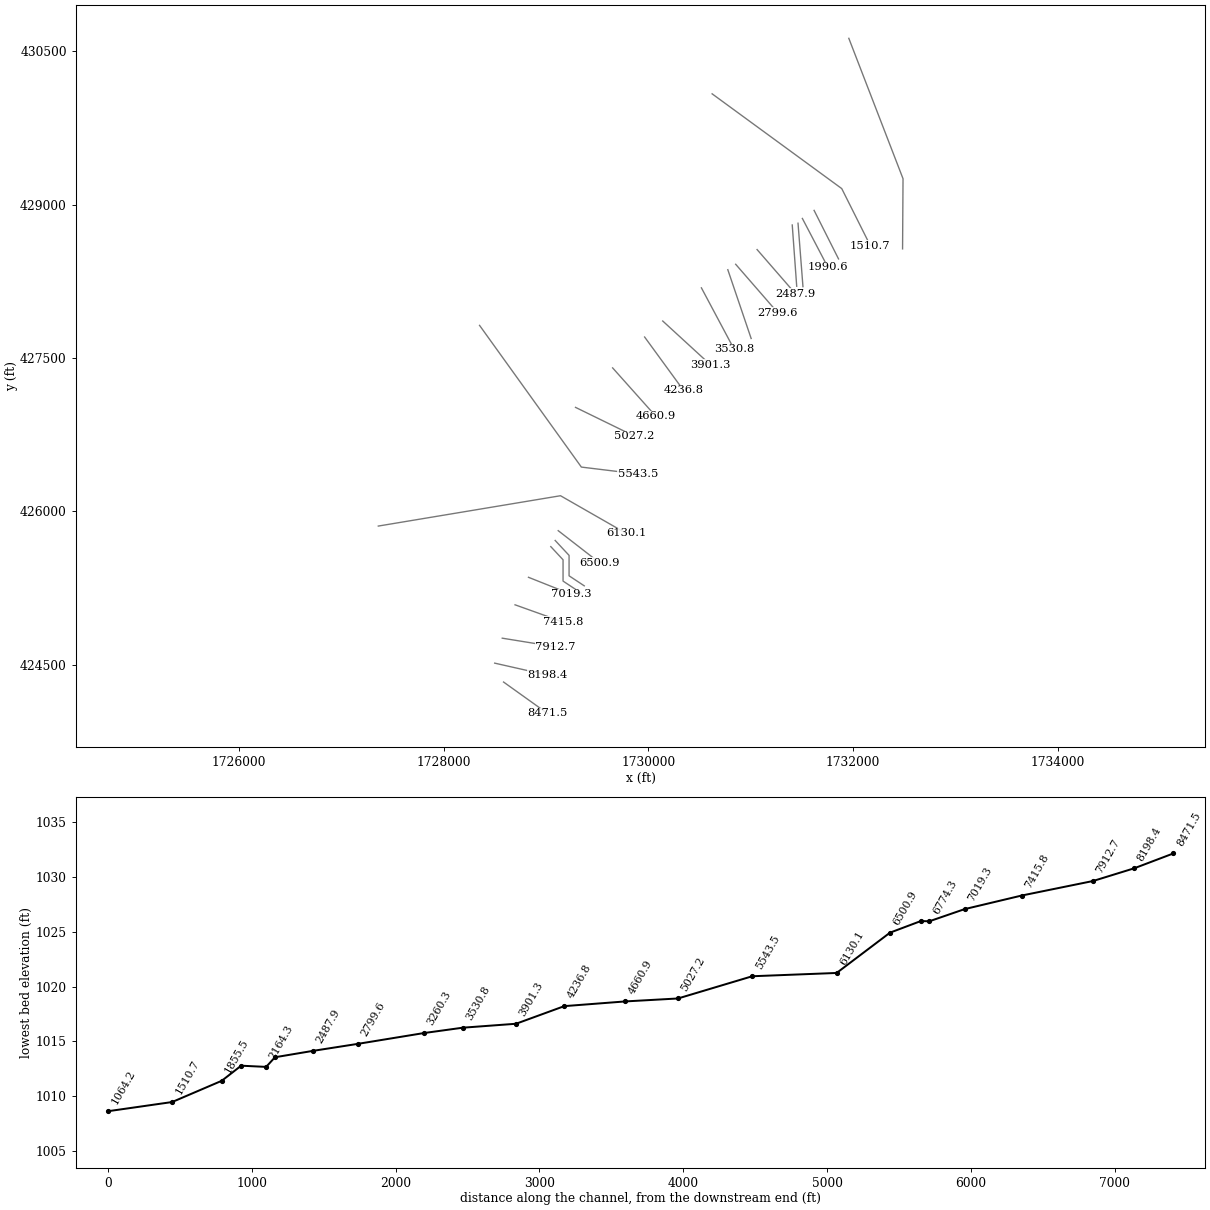
HEC-RAS study SouthFork.prj: SouthFork

--- SouthFork.g01 (geometry) --- (continued)

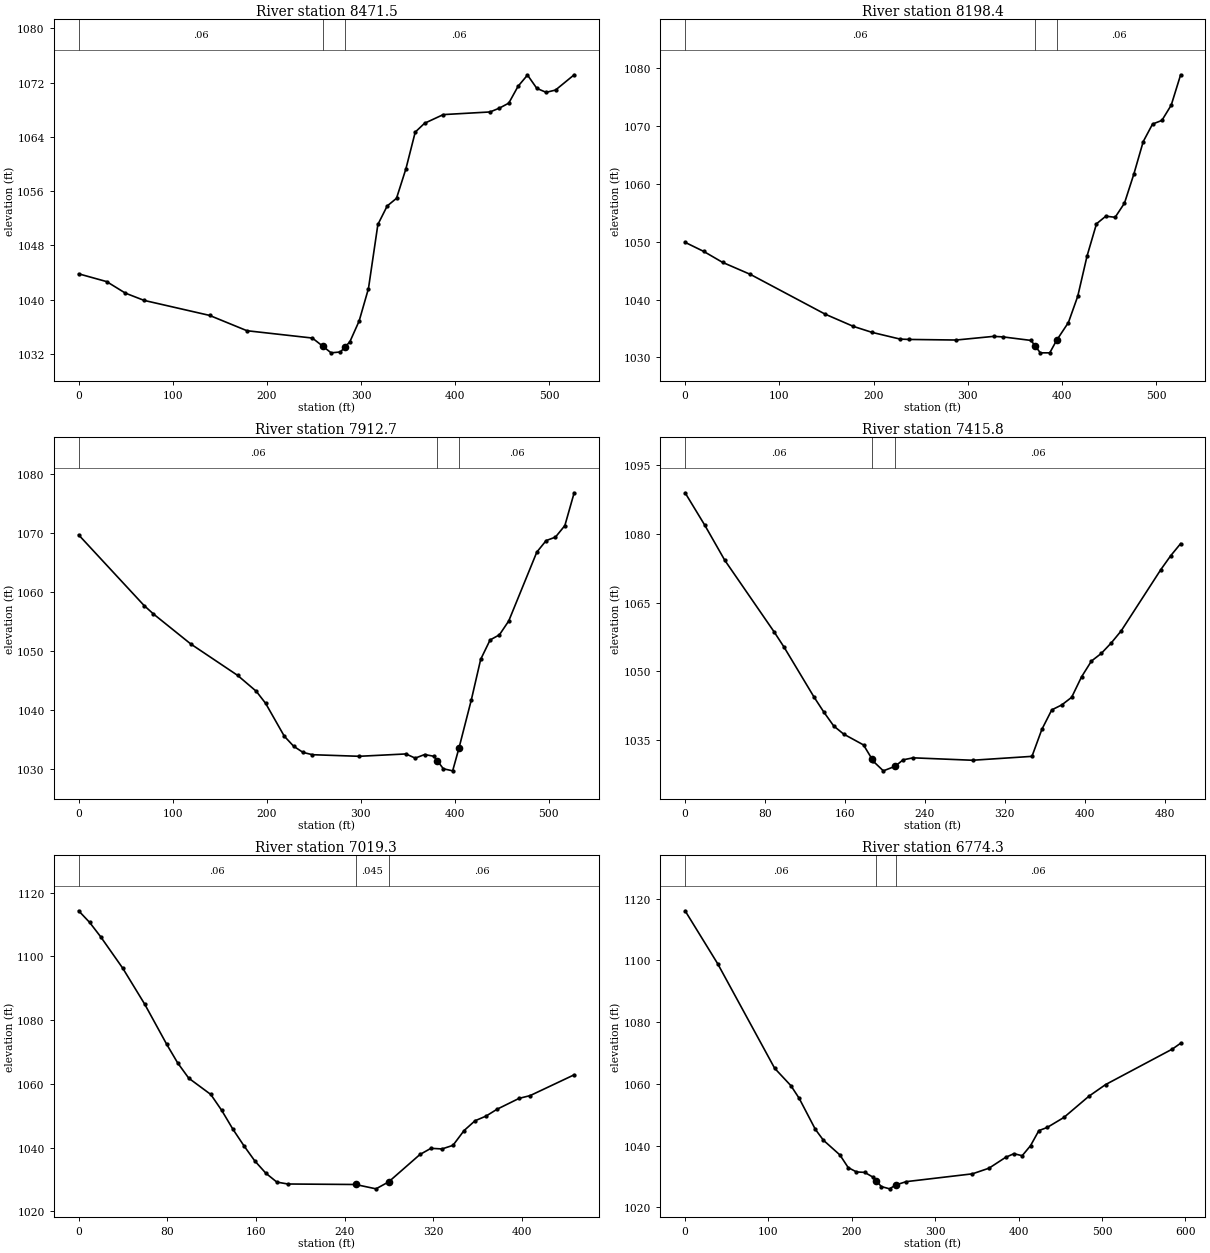
Type RM Length L Ch R = 1 ,8471.5  ,263.9,273,283.1
XS GIS Cut Line= 2
     1728586.258      424329.641      1729014.36       424022.92
#Sta/Elev= 30
       0 1043.81    29.8 1042.66    49.7 1040.96    69.6 1039.89   139.1 1037.68
   178.9 1035.42   248.4 1034.34   259.6 1033.12   268.3 1032.16   278.2 1032.29
   282.6 1032.95   288.2 1033.78   298.1 1036.86     308 1041.64     318 1051.08
   327.9 1053.81   337.8 1054.94   347.8 1059.29   357.7  1064.7   367.6    1066
   387.5 1067.28   437.2 1067.67   447.2 1068.24   457.1 1068.97     467 1071.46
     477 1073.11   486.9 1071.15   496.8 1070.56   506.8  1070.9   526.6 1073.15
#Mann= 3 , 0 , 0
       0     .06       0   259.6    .045       0   282.6     .06       0
Bank Sta=259.6,282.6
XS Rating Curve= 0 ,0
Exp/Cntr=0.3,0.1

Type RM Length L Ch R = 1 ,8198.4  ,284.1,285.7,287.5
XS GIS Cut Line= 2
     1728499.714      424514.499     1729012.557      424398.217
#Sta/Elev= 30
       0 1049.86    19.8 1048.29    39.7 1046.41    69.4 1044.32   148.8 1037.46
   178.6 1035.36   198.4 1034.33   228.2 1033.17   238.1 1033.11   287.7 1033.01
   327.4 1033.64   337.3 1033.55   367.1 1032.94   371.2 1032.05     377  1030.8
     387  1030.8   394.2 1032.94   406.8 1036.03   416.7 1040.56   426.6 1047.51
   436.6 1053.06   446.5 1054.37   456.4 1054.18   466.3 1056.62   476.2 1061.61
   486.2 1067.24   496.1 1070.26     506 1070.89   515.9 1073.52   525.9 1078.76
#Mann= 3 , 0 , 0
       0     .06       0   371.2    .045       0   394.2     .06       0
Bank Sta=371.2,394.2
XS Rating Curve= 0 ,0
Exp/Cntr=0.3,0.1

Type RM Length L Ch R = 1 ,7912.7  ,502.1,496.9,492
XS GIS Cut Line= 2
     1728573.633      424758.664     1729093.789      424674.406
#Sta/Elev= 30
       0 1069.72    69.6 1057.72    79.5 1056.29   119.3 1051.18     169 1045.86
   188.9 1043.15   198.8 1041.11   218.7 1035.52   228.7 1033.81   238.6 1032.77
   248.6 1032.38   298.3 1032.11     348 1032.51   357.9  1031.8   367.9 1032.41
   377.8 1032.11   381.4 1031.35   387.8 1029.99   397.7 1029.64   404.4  1033.5
   417.6 1041.73   427.5 1048.58   437.5 1051.87   447.4 1052.74   457.3 1055.09
   487.2  1066.8   497.1 1068.75     507 1069.34     517  1071.3   526.9 1076.87
#Mann= 3 , 0 , 0
       0     .06       0   381.4    .045       0   404.4     .06       0
Bank Sta=381.4,404.4
XS Rating Curve= 0 ,0
Exp/Cntr=0.3,0.1

Type RM Length L Ch R = 1 ,7415.8  ,388.7,396.5,395
XS GIS Cut Line= 2
     1728698.493      425085.222     1729165.368      424917.776
#Sta/Elev= 30
       0 1088.98    19.8 1081.87    39.7 1074.26    89.3 1058.57    99.2 1055.25
     129 1044.43   138.9 1041.12   148.8 1038.09   158.7 1036.33   178.6 1033.96
   187.1 1030.88   188.5 1030.37   198.4 1028.31   210.1 1029.29   218.2 1030.71
   228.2 1031.15   287.7 1030.62   347.2 1031.47   357.1 1037.36     367 1041.61
     377 1042.69   386.9 1044.35   396.8 1048.81   406.7 1052.26   416.6 1053.93
   426.6 1056.23   436.5 1058.85   476.2 1072.23   486.1 1075.26     496 1077.89
#Mann= 3 , 0 , 0
       0     .06       0   187.1    .045       0   210.1     .06       0
Bank Sta=187.1,210.1
XS Rating Curve= 0 ,0
Exp/Cntr=0.3,0.1

Type RM Length L Ch R = 1 ,7019.3  ,277.1,245,213.7
XS GIS Cut Line= 2
     1728829.642      425354.426     1729245.029      425188.624
#Sta/Elev= 30
       0 1114.32     9.9 1110.68    19.9 1106.16    39.8 1096.31    59.6 1085.04
    79.5 1072.42    89.4 1066.58    99.4 1061.79   119.3 1056.68   129.2 1051.66
   139.2 1045.81   149.1 1040.64     159 1035.84     169 1031.97   178.9 1029.19
   188.8 1028.59     2501028.432   268.4 1027.07   279.8 1029.24   308.1 1037.85
     318 1039.78     328 1039.59   337.9 1040.72   347.9 1045.35   357.8 1048.43
   367.7 1049.89   377.7 1052.05   397.6 1055.46   407.5 1056.32   447.3 1062.85
#Mann= 3 , 0 , 0
       0     .06       0     250    .045       0   279.8     .06       0
Bank Sta=250,279.8
XS Rating Curve= 0 ,0
Exp/Cntr=0.3,0.1

Type RM Length L Ch R = 1 ,6774.3  ,59.3,59.3,59.3
XS GIS Cut Line= 4
     1729047.605      425654.473     1729167.207      425525.758
     1729167.207      425317.221     1729342.312      425201.362
#Sta/Elev= 30
       0 1116.06      39 1098.94   107.4 1065.02   126.9 1059.38   136.7 1055.33
   156.2 1045.23   165.9  1041.7   185.6 1036.95   195.6 1032.84   205.5 1031.44
   215.4 1031.29   225.4 1029.73   229.4 1028.51   235.3  1026.7   245.2 1025.96
   252.4 1027.19   265.1 1028.29   344.5 1030.82   364.4 1032.65   384.2 1036.14
   394.2 1037.35   404.2  1036.7   414.2 1039.94   424.2 1044.83   434.2 1045.85
   454.2 1049.09   484.2 1055.97   504.2 1059.74   584.2 1071.24   594.2 1073.14
#Mann= 3 , 0 , 0
       0     .06       0   229.4    .045       0   252.4     .06       0
Bank Sta=229.4,252.4
XS Rating Curve= 0 ,0
Exp/Cntr=0.3,0.1

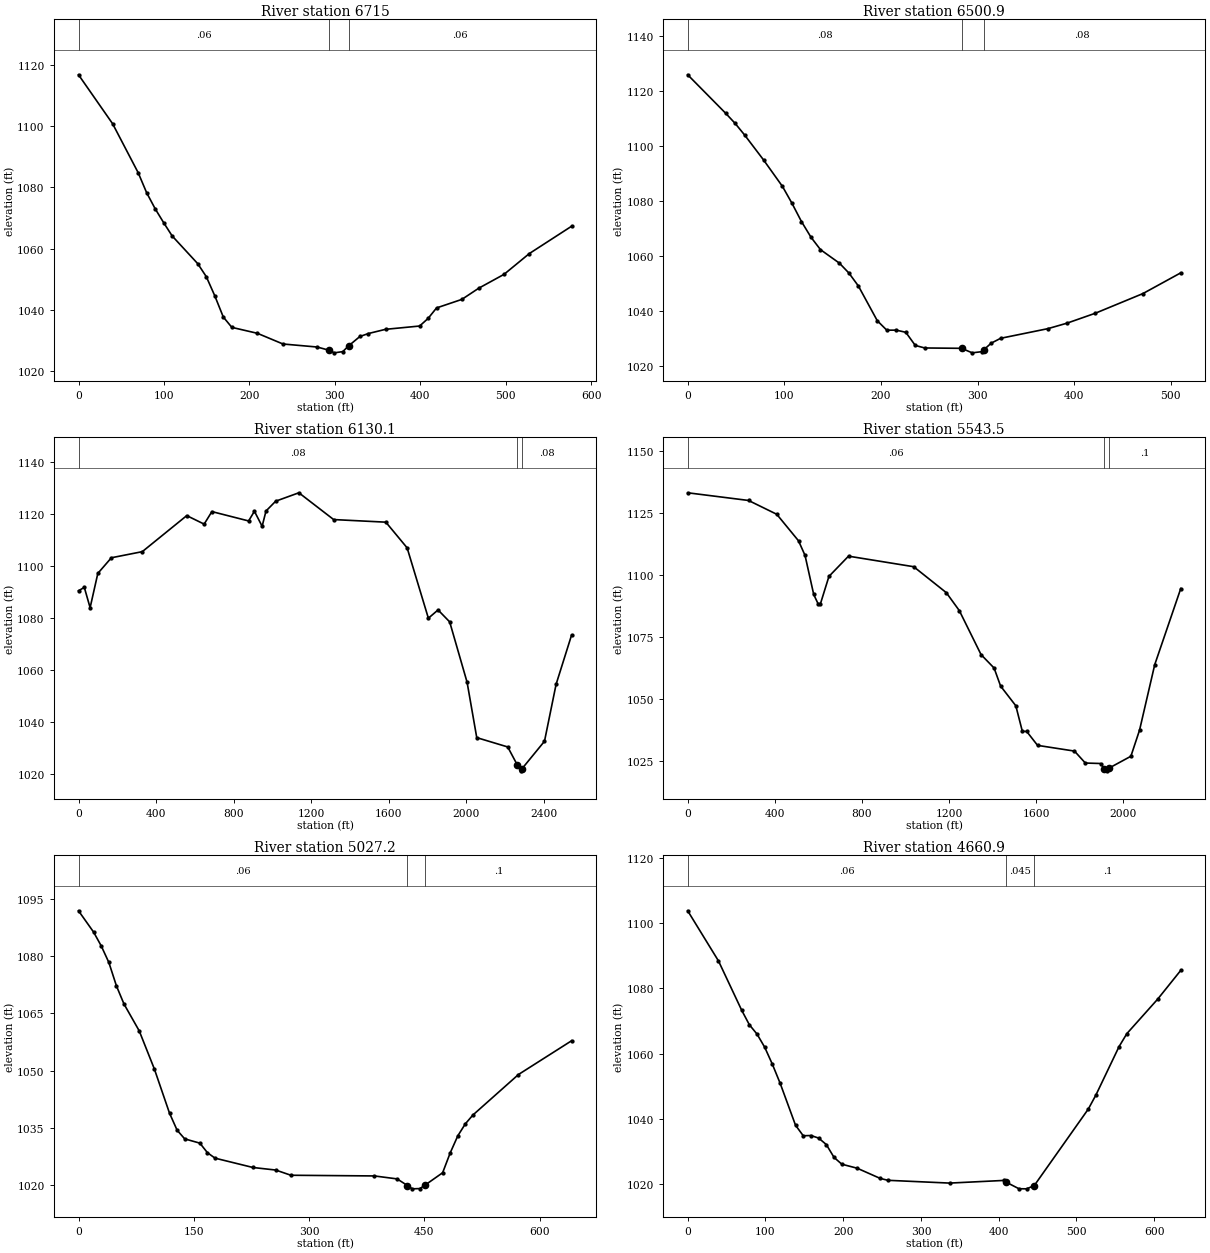
Type RM Length L Ch R = 1 ,6715    ,189.8,214.1,238.6
XS GIS Cut Line= 4
     1729090.343      425714.762     1729225.992      425568.779
     1729225.992      425368.914     1729374.205      425270.848
#Sta/Elev= 30
       0 1116.82    39.9 1100.83    69.8 1084.83    79.7  1078.3    89.7 1073.04
    99.6 1068.51   109.6 1064.16   139.5 1055.11   149.5 1050.87   159.4 1044.64
   169.4 1037.68   179.4  1034.3   209.3 1032.36   239.2 1028.87   279.2 1027.88
   292.9 1026.85   299.2 1025.98   309.2 1026.38   315.9 1028.23   329.2 1031.32
   339.2 1032.29   359.2 1033.66   399.1 1034.74     409 1037.22   418.9 1040.65
   448.5 1043.44   468.3  1047.1   497.9 1051.63   527.5 1058.42   576.9 1067.34
#Mann= 3 , 0 , 0
       0     .06       0   292.9    .045       0   315.9     .06       0
Bank Sta=292.9,315.9
XS Rating Curve= 0 ,0
Exp/Cntr=0.3,0.1

Type RM Length L Ch R = 1 ,6500.9  ,366.7,370.8,374.4
XS GIS Cut Line= 2
      1729119.91      425810.628     1729522.715      425497.472
#Sta/Elev= 30
       0 1125.93    39.2 1111.99    49.1 1108.27    58.9 1104.06    78.5    1095
    98.1 1085.36   107.9 1079.26   117.7 1072.63   127.6 1066.91   137.4 1062.41
     157  1057.5   166.8 1053.92   176.6 1049.22   196.2 1036.58     206 1033.16
   215.9 1033.16   225.7 1032.38   235.5 1027.61   245.3 1026.69   283.4 1026.56
   294.4 1024.92   304.2 1025.34   306.4 1026.03     314 1028.42   323.8  1030.2
   372.8 1033.71   392.5  1035.7   421.9 1039.32     471 1046.44   510.2 1053.98
#Mann= 3 , 0 , 0
       0     .08       0   283.4    .045       0   306.4     .08       0
Bank Sta=283.4,306.4
XS Rating Curve= 0 ,0
Exp/Cntr=0.3,0.1

Type RM Length L Ch R = 1 ,6130.1  ,574.7,586.6,597.6
XS GIS Cut Line= 3
     1727363.317      425855.665     1729142.335      426152.518
     1729782.671      425785.082
#Sta/Elev= 30
       0 1090.54    29.9 1091.85    59.8 1084.03    99.6 1097.22   169.4 1103.24
   328.8 1105.59     558 1119.46   647.7 1116.19   687.6 1121.01   876.9 1117.41
   906.8 1121.14   946.6 1115.36   966.6 1121.24  1016.4 1125.01    1136 1128.25
  1315.3 1117.94  1584.4 1116.94    1694 1107.06  1803.6 1079.98  1853.5 1083.16
  1913.4 1078.57  2003.2 1055.33    2053 1034.02  2212.7 1030.43  2262.6 1023.42
  2282.5 1021.24  2285.6 1021.99  2402.2 1032.63  2462.1 1054.56  2541.9  1073.5
#Mann= 3 , 0 , 0
       0     .08       0  2262.6    .045       0  2285.6     .08       0
Bank Sta=2262.6,2285.6
XS Rating Curve= 0 ,0
Exp/Cntr=0.3,0.1

Type RM Length L Ch R = 1 ,5543.5  ,524.6,516.3,506.4
XS GIS Cut Line= 3
     1728351.957      427819.228     1729346.022      426432.807
     1729899.576      426365.197
#Sta/Elev= 30
       0 1133.16   279.3 1130.06     409 1124.48   508.8 1113.78   538.7  1107.9
   578.6 1092.12   598.6 1088.37   608.6 1088.12   648.5 1099.41   738.3 1107.58
  1037.6 1103.32  1187.2 1092.86    1247 1085.61  1346.8 1067.85  1406.7 1062.42
  1436.6 1055.14  1506.4  1047.2  1536.4 1036.87  1556.3 1036.84  1606.2 1031.22
  1775.7 1028.91  1825.5 1024.09  1895.2  1023.9  1912.4 1021.88    1925 1020.94
  1935.4 1022.09  2034.6 1026.82  2074.4 1037.36  2144.1 1063.79  2263.6 1094.51
#Mann= 3 , 0 , 0
       0     .06       0  1912.4    .045       0  1935.4      .1       0
Bank Sta=1912.4,1935.4
XS Rating Curve= 0 ,0
Exp/Cntr=0.3,0.1

Type RM Length L Ch R = 1 ,5027.2  ,376.6,366.3,355.9
XS GIS Cut Line= 2
     1729288.993       427016.98     1729865.326      426734.978
#Sta/Elev= 30
       0 1091.99    19.7 1086.37    29.6 1082.74    39.5  1078.4    49.4 1072.22
    59.2 1067.48      79 1060.43    98.7 1050.41   118.4 1038.81   128.3 1034.32
   138.2 1032.04   157.9 1030.92   167.8  1028.4   177.7 1026.97     227 1024.52
   256.6 1023.85   276.4 1022.48     385  1022.3   414.6 1021.52     428 1019.78
   434.3 1018.91   444.2 1018.98     451  1019.9   473.8 1023.14   483.7 1028.38
   493.6 1032.86   503.4 1036.01   513.3 1038.33   572.5 1048.96   641.6 1057.83
#Mann= 3 , 0 , 0
       0     .06       0     428    .045       0     451      .1       0
Bank Sta=428,451
XS Rating Curve= 0 ,0
Exp/Cntr=0.3,0.1

Type RM Length L Ch R = 1 ,4660.9  ,426.6,424.1,421.4
XS GIS Cut Line= 2
     1729651.239      427403.376     1730073.088      426929.955
#Sta/Elev= 30
       0 1103.75    39.6  1088.4    69.4 1073.33    79.3 1068.87    89.2    1066
    99.1 1061.96     109 1056.73   118.9 1050.96   138.7 1038.11   148.6 1034.89
   158.5 1034.96   168.4 1034.18   178.3 1032.19   188.2 1028.27   198.2 1026.18
     218 1024.95   247.7 1021.82   257.6 1021.25   336.9  1020.4   406.2 1021.21
     410 1020.63     426 1018.67   435.9 1018.64   445.7 1019.64   515.2 1043.06
   525.1 1047.41   554.8  1062.2   564.8 1066.15   604.4  1076.7   634.1 1085.51
#Mann= 3 , 0 , 0
       0     .06       0     410    .045       0   445.7      .1       0
Bank Sta=410,445.7
XS Rating Curve= 0 ,0
Exp/Cntr=0.3,0.1

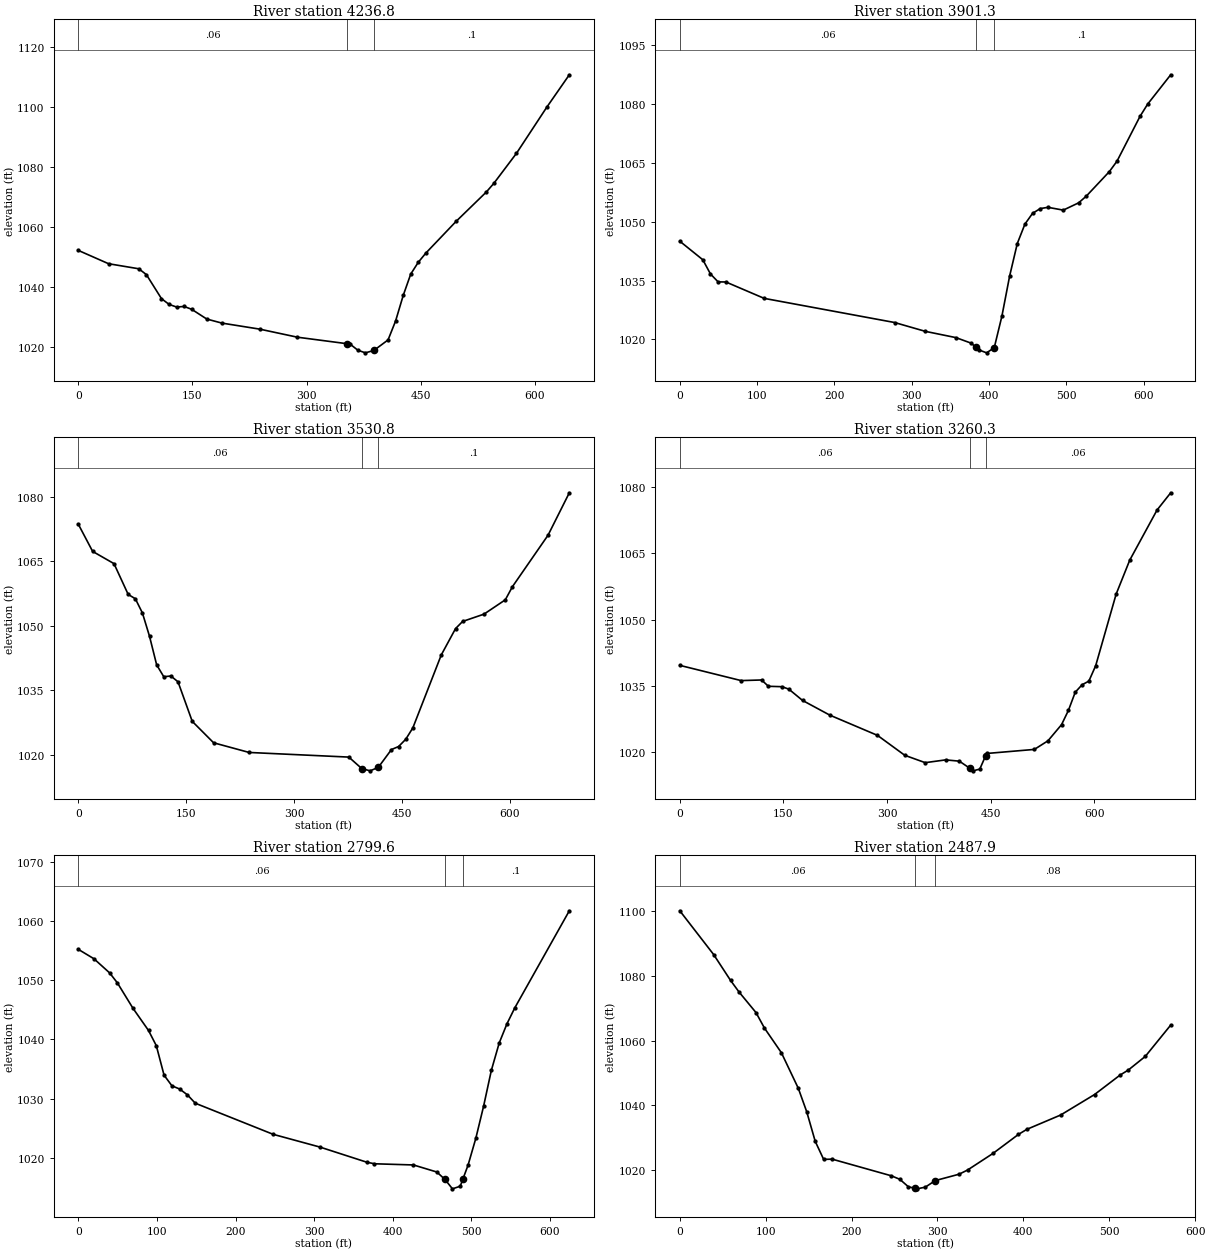
Type RM Length L Ch R = 1 ,4236.8  ,330.5,335.5,340.4
XS GIS Cut Line= 2
     1729963.636      427705.468     1730343.394      427183.626
#Sta/Elev= 30
       0 1052.28    39.7 1047.86    79.4 1046.18    89.4 1044.23   109.2 1036.25
   119.2 1034.33   129.1 1033.45     139 1033.64   148.9  1032.7   168.8 1029.45
   188.6 1028.11   238.3  1026.1     288 1023.41   353.4 1021.24   357.4 1021.07
   367.4 1019.08   377.3 1018.21   388.4    1019   407.1 1022.51     417  1028.8
     427 1037.29   436.9 1044.41   446.8 1048.33   456.7 1051.38   496.5 1061.94
   536.2  1071.7   546.1 1074.58   575.9 1084.59   615.6 1099.88   645.4 1110.73
#Mann= 3 , 0 , 0
       0     .06       0   353.4    .045       0   388.4      .1       0
Bank Sta=353.4,388.4
XS Rating Curve= 0 ,0
Exp/Cntr=0.3,0.1

Type RM Length L Ch R = 1 ,3901.3  ,381.1,370.5,361.3
XS GIS Cut Line= 2
     1730140.565      427861.983      1730608.21      427432.146
#Sta/Elev= 30
       0 1045.05    29.8 1040.32    39.7  1036.7    49.6 1034.68    59.6 1034.66
   109.2 1030.48   277.9 1024.33   317.6 1022.08   357.3 1020.48   377.1 1019.06
   383.1 1018.03   387.1 1017.34     397  1016.6   406.1 1017.81   406.9 1017.92
   416.8 1025.97   426.8 1036.19   436.7 1044.46   446.6 1049.42   456.5 1052.16
   466.5 1053.37   476.4 1053.68   496.2 1052.97   516.1 1054.83     526 1056.54
   555.8 1062.78   565.7 1065.44   595.5 1076.87   605.4 1079.99   635.2 1087.46
#Mann= 3 , 0 , 0
       0     .06       0   383.1    .045       0   406.1      .1       0
Bank Sta=383.1,406.1
XS Rating Curve= 0 ,0
Exp/Cntr=0.3,0.1

Type RM Length L Ch R = 1 ,3530.8  ,346.5,270.4,265.4
XS GIS Cut Line= 2
     1730518.148      428186.513     1730838.613      427583.768
#Sta/Elev= 30
       0 1073.62    19.8 1067.33    49.5 1064.48    69.2 1057.32    79.2  1056.3
      89    1053    98.9 1047.56   108.8 1040.92   118.7 1038.15   128.6 1038.32
   138.5 1036.97   158.3 1027.76     188 1022.77   237.4 1020.52     376 1019.44
     394 1016.77   405.6 1016.24     417 1017.05   435.3  1021.2   445.2  1021.9
   455.1 1023.58     465 1026.23   504.6 1043.24   524.4 1049.36   534.2 1051.02
   563.9 1052.72   593.6 1056.06   603.5 1059.12     653  1071.1   682.6 1080.98
#Mann= 3 , 0 , 0
       0     .06       0     394    .045       0     417      .1       0
Bank Sta=394,417
XS Rating Curve= 0 ,0
Exp/Cntr=0.3,0.1

Type RM Length L Ch R = 1 ,3260.3  ,377.1,460.7,386.2
XS GIS Cut Line= 2
     1730775.963      428364.081     1731003.849      427690.948
#Sta/Elev= 30
       0 1039.63    88.8 1036.18   118.4 1036.32   128.3 1034.89     148  1034.8
   157.9 1034.24   177.7 1031.69   217.2 1028.36   286.2 1023.78   325.7 1019.27
   355.3  1017.6   384.9 1018.23   404.7 1017.94   419.6 1016.36   424.4 1015.75
   434.3 1016.14   442.6 1019.11   444.2 1019.68   513.3  1020.6     533 1022.55
   552.7 1026.21   562.6 1029.43   572.5 1033.55   582.4 1035.24   592.2 1036.06
   602.1 1039.56   631.7 1055.76   651.4 1063.45   690.9 1074.79   710.7  1078.7
#Mann= 3 , 0 , 0
       0     .06       0   419.6    .045       0   442.6     .06       0
Bank Sta=419.6,442.6
XS Rating Curve= 0 ,0
Exp/Cntr=0.3,0.1

Type RM Length L Ch R = 1 ,2799.6  ,314.7,311.8,308.3
XS GIS Cut Line= 2
     1730852.867      428417.048     1731262.131      427945.231
#Sta/Elev= 30
       0 1055.17    19.8 1053.59    39.7 1051.21    49.6 1049.52    69.4 1045.24
    89.2 1041.49    99.1 1038.93     109 1033.94     119 1032.15   128.9  1031.6
   138.8 1030.61   148.7 1029.21   247.8 1023.96   307.3 1021.81   366.8 1019.26
   376.7 1018.99   426.3 1018.79     456  1017.6   466.3 1016.36   475.9 1014.76
   485.8  1015.2   489.3 1016.45   495.7 1018.73   505.6 1023.27   515.5 1028.69
   525.4 1034.76   535.4 1039.38   545.3 1042.63   555.2  1045.3   624.6 1061.69
#Mann= 3 , 0 , 0
       0     .06       0   466.3    .045       0   489.3      .1       0
Bank Sta=466.3,489.3
XS Rating Curve= 0 ,0
Exp/Cntr=0.3,0.1

Type RM Length L Ch R = 1 ,2487.9  ,276.9,262.5,248.6
XS GIS Cut Line= 2
     1731061.835      428560.973     1731436.389       428129.17
#Sta/Elev= 30
       0  1100.2    39.4 1086.66    59.1 1078.65      69 1075.05    88.7  1068.7
    98.6 1063.88   118.3 1056.26     138 1045.24   147.8 1037.98   157.7 1028.82
   167.5 1023.24   177.4 1023.31   246.4 1018.15   256.2 1017.07   266.1 1014.77
   274.4 1014.23     276 1014.12   285.8 1014.63   297.4 1016.67   325.2 1018.65
   335.1 1019.95   364.6 1025.07   394.2 1030.95   404.1 1032.54   443.5 1036.98
   482.9 1043.31   512.5 1049.31   522.3 1050.91     542 1055.12   571.6 1064.81
#Mann= 3 , 0 , 0
       0     .06       0   274.4    .045       0   297.4     .08       0
Bank Sta=274.4,297.4
XS Rating Curve= 0 ,0
Exp/Cntr=0.3,0.1

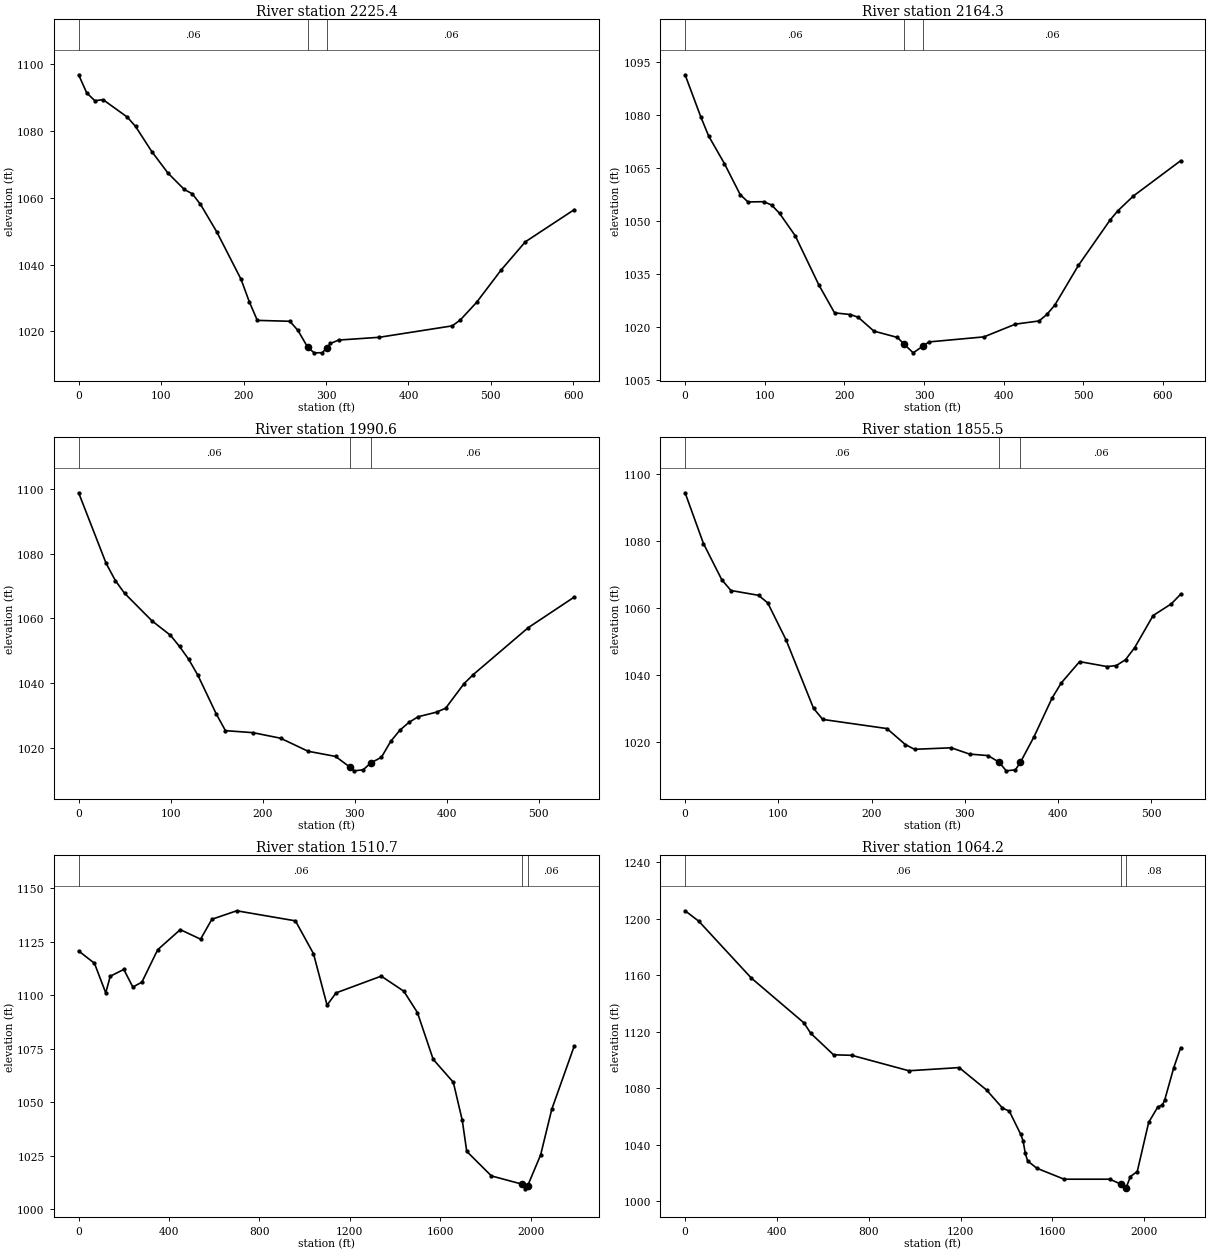
Type RM Length L Ch R = 1 ,2225.4  ,60.7,61.1,61.2
XS GIS Cut Line= 2
     1731405.037      428801.544     1731448.612      428202.159
#Sta/Elev= 30
       0  1096.9     9.8 1091.47    19.7 1089.12    29.6 1089.44    59.1  1084.2
      69 1081.42    88.7 1073.89   108.4 1067.41   128.1 1062.53   137.9 1061.21
   147.8 1058.04   167.5 1049.82     197 1035.58   206.9  1028.9   216.7 1023.27
   256.2    1023     266 1020.25   277.9 1015.18   285.7 1013.54   295.6 1013.58
   300.9 1015.07   305.4 1016.34   315.3 1017.37   364.5  1018.2   453.2 1021.63
     463 1023.42   482.7 1028.69   512.3 1038.34   541.8 1046.83     601 1056.45
#Mann= 3 , 0 , 0
       0     .06       0   277.9    .045       0   300.9     .06       0
Bank Sta=277.9,300.9
XS Rating Curve= 0 ,0
Exp/Cntr=0.3,0.1

Type RM Length L Ch R = 1 ,2164.3  ,162.7,173.7,184.3
XS GIS Cut Line= 2
      1731461.46      428818.905     1731509.667      428198.373
#Sta/Elev= 30
       0  1091.4    19.8 1079.43    29.6 1074.05    49.4 1066.25    69.2 1057.46
      79 1055.39    98.8 1055.46   108.7 1054.51   118.6 1052.17   138.3 1045.82
     168 1031.89   187.7 1023.98   207.5 1023.51   217.4 1022.74   237.1 1018.82
   266.7 1017.02   275.3 1015.06   286.5 1012.66   298.3  1014.5   306.3 1015.75
   375.4 1017.18   414.9 1020.79   444.6 1021.69   454.4 1023.54   464.3 1026.16
     494 1037.42   533.5 1050.18   543.4 1052.86   563.1 1057.08   622.4 1067.06
#Mann= 3 , 0 , 0
       0     .06       0   275.3    .045       0   298.3     .06       0
Bank Sta=275.3,298.3
XS Rating Curve= 0 ,0
Exp/Cntr=0.3,0.1

Type RM Length L Ch R = 1 ,1990.6  ,135.5,135.1,134.6
XS GIS Cut Line= 2
     1731503.988      428865.502     1731753.173       428387.88
#Sta/Elev= 30
       0 1098.93    29.9 1077.05    39.9 1071.74    49.9  1067.8    79.8 1059.23
    99.8 1054.78   109.7  1051.3   119.7  1047.3   129.7 1042.34   149.6 1030.41
   159.6 1025.22   189.6  1024.6   219.5 1022.88   249.4 1018.84   279.3 1017.24
   294.6 1013.98   299.3 1012.77   309.3 1013.09   317.6 1015.21   329.2 1016.99
   339.2 1021.88   349.2 1025.35   359.1  1027.8   369.1 1029.53   389.1 1030.96
     399 1032.18     419  1039.8     429 1042.59   488.8 1057.14   538.7  1066.6
#Mann= 3 , 0 , 0
       0     .06       0   294.6    .045       0   317.6     .06       0
Bank Sta=294.6,317.6
XS Rating Curve= 0 ,0
Exp/Cntr=0.3,0.1

Type RM Length L Ch R = 1 ,1855.5  ,344.7,344.8,344.8
XS GIS Cut Line= 2
     1731618.479      428944.357     1731856.953      428469.616
#Sta/Elev= 30
       0 1094.41    19.7 1079.24    39.4 1068.41    49.2 1065.23    78.7  1063.8
    88.6 1061.53   108.2 1050.52   137.7 1030.06   147.6 1026.74   216.4 1024.01
   236.1 1019.25     246 1017.82   285.3 1018.27     305 1016.39   324.7 1015.95
   336.6    1014   344.3 1011.39   354.2  1011.7   359.6    1014   373.9 1021.45
   393.5 1033.14   403.4 1037.66     423    1044   452.6 1042.51   462.4 1042.84
   472.2 1044.57   482.1 1048.21   501.8 1057.76   521.4 1061.27   531.3 1064.12
#Mann= 3 , 0 , 0
       0     .06       0   336.6    .045       0   359.6     .06       0
Bank Sta=336.6,359.6
XS Rating Curve= 0 ,0
Exp/Cntr=0.3,0.1

Type RM Length L Ch R = 1 ,1510.7  ,459.3,446.6,433.1
XS GIS Cut Line= 3
     1730622.791      430084.853     1731888.338      429157.731
     1732167.318      428599.769
#Sta/Elev= 30
       0 1120.62      70 1114.87   119.9 1101.03   139.9  1108.8   199.8    1112
   239.8 1103.76   279.8 1106.03   349.7 1121.18   449.7 1130.59   539.6 1126.13
   589.6 1135.43   699.5  1139.4   959.3 1134.69  1039.2 1119.34  1099.2 1095.31
  1139.1 1101.03    1339 1108.86  1438.9  1101.8  1498.9 1091.86  1568.8 1069.97
  1657.9 1059.26  1697.5 1041.43  1717.3 1026.95  1826.3 1015.49  1963.6 1011.59
  1974.8 1009.45  1986.6 1010.83  2044.1 1025.27  2093.6 1046.68  2192.6 1076.11
#Mann= 3 , 0 , 0
       0     .06       0  1963.6    .045       0  1986.6     .06       0
Bank Sta=1963.6,1986.6
XS Rating Curve= 0 ,0
Exp/Cntr=0.3,0.1

Type RM Length L Ch R = 1 ,1064.2  ,1067.3,1064.2,1060.5
XS GIS Cut Line= 3
     1731957.513      430627.908     1732486.739      429254.407
     1732482.252      428567.975
#Sta/Elev= 30
       0 1205.71    59.7 1198.31   288.4 1158.03   517.2 1126.33     547 1118.93
   646.5 1103.63     726 1103.26   974.7 1092.31  1193.5 1094.56  1312.8 1078.71
  1382.4 1065.89  1412.3 1063.66    1462 1047.18  1471.9 1042.78  1481.9 1033.67
  1491.8 1028.44  1531.6 1023.24    1651 1015.44    1850 1015.44  1898.1 1011.92
  1919.6 1008.61  1921.1 1009.42  1939.5 1017.31  1969.4 1020.86  2019.1  1055.7
  2058.9 1066.64  2078.8 1067.99  2088.7 1071.41  2128.5  1094.5  2158.4 1108.59
#Mann= 3 , 0 , 0
       0     .06       0  1898.1    .045       0  1921.1     .08       0
Bank Sta=1898.1,1921.1
XS Rating Curve= 0 ,0
Exp/Cntr=0.3,0.1

Chan Stop Cuts=-1
Use User Specified Reach Order=0
Composite Channel Slope=5